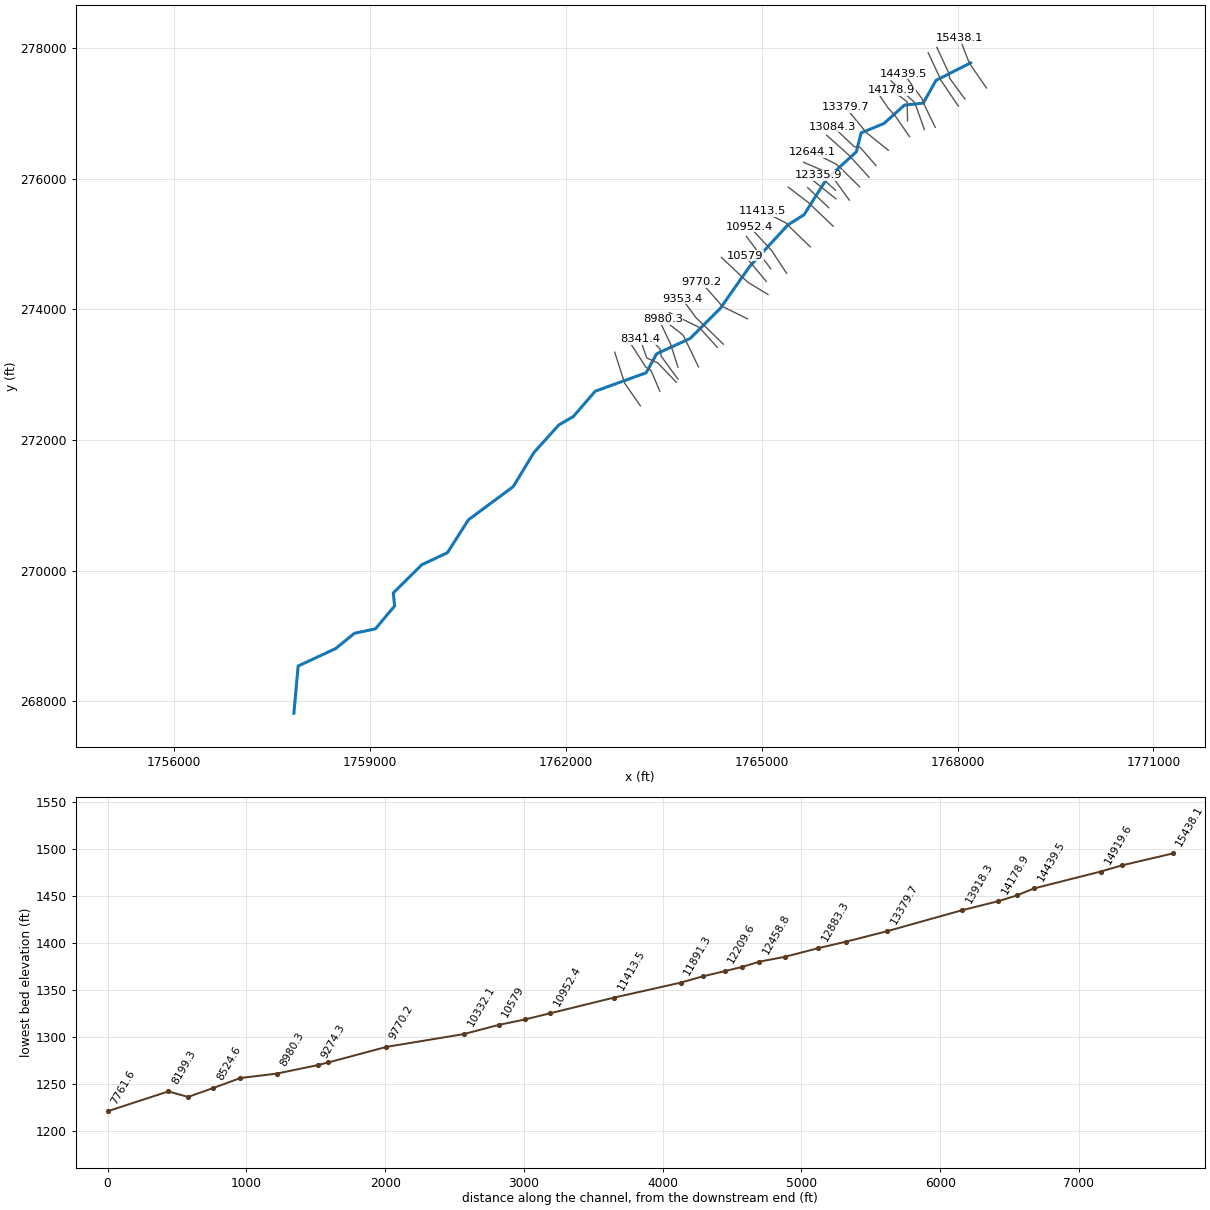
--- ToneyFk1.prj (project) ---

Proj Title=ToneyFk1
Current Plan=p01
Default Exp/Contr=0,0
English Units
Geom File=g01
Flow File=f01
Plan File=p01
BEGIN DESCRIPTION:
END DESCRIPTION:
DSS Export Rating Curves= 0
DSS Export Rating Curve Sorted= 0
DSS Export Volume Flow Curves= 0
DXF OffsetX= 0
DXF OffsetY= 0
DXF ScaleX= 0
DXF ScaleY= 0

--- ToneyFk1.p01 (plan) ---

Plan Title=Floodplain
Program Version=4.00
Geom File=g01
Flow File=f01
K Sum by GR=0
Std Step Tol=0.01
Critical Tol=0.01
Num of Std Step Trials=20
Max Error Tol=0.3
Flow Tol Ratio=0.001
Split Flow NTrial=30
Split Flow Tol=0.02
Split Flow Ratio=0.02
Log Output Level=0
Friction Slope Method=1
Unsteady Friction Slope Method=2
Unsteady Bridges Friction Slope Method=1
Global Log Level=0
CheckData=False
Run HTab=0
Run UNet=0
Run PostProcess=0
UNET Theta=0
UNET Theta Warmup=0
UNET ZTol=0
UNET ZSATol=0
UNET MxIter=0
UNET MaxInSteps=0
UNET DtIC=0
UNET DtMin=0
UNET MaxCRTS=0
UNET WFStab=0
UNET SFStab=0
UNET WFX=0
UNET SFX=0
UNET DSS MLevel=0
UNET DZMax Abort=0
UNET Convert EG Bridges=0
UNET Use Existing IB Tables=0
UNET Froude Limit=0
UNET Froude Power=0
Write IC File=0
Echo Input=False
Echo Output=False
Write Detailed=0

--- ToneyFk1.f01 (steady flow) ---

Flow Title=NFF Regression Equation
Program Version=4.00
Number of Profiles=1
Profile Names=P100yr
River Rch & RM=ToneyFk1,Main      ,15438.1
     355
River Rch & RM=ToneyFk1,Main      ,15438.1
555.6296
River Rch & RM=ToneyFk1,Main      ,14919.6
357.6627
River Rch & RM=ToneyFk1,Main      ,14919.6
561.9253
River Rch & RM=ToneyFk1,Main      ,14313.5
396.8591
River Rch & RM=ToneyFk1,Main      ,14313.5
614.0286
River Rch & RM=ToneyFk1,Main      ,13379.7
427.3100
River Rch & RM=ToneyFk1,Main      ,13379.7
653.4616
River Rch & RM=ToneyFk1,Main      ,13084.3
519.4330
River Rch & RM=ToneyFk1,Main      ,13084.3
772.8511
River Rch & RM=ToneyFk1,Main      ,12458.8
538.1221
River Rch & RM=ToneyFk1,Main      ,12458.8
797.0295
River Rch & RM=ToneyFk1,Main      ,10952.4
588.4542
River Rch & RM=ToneyFk1,Main      ,10952.4
862.2479
River Rch & RM=ToneyFk1,Main      ,8524.6
941.3308
River Rch & RM=ToneyFk1,Main      ,8524.6
652.7057
River Rch & RM=ToneyFk1,Main      ,8199.3
1044.298
River Rch & RM=ToneyFk1,Main      ,8199.3
735.9578
River Rch & RM=ToneyFk1,Main      ,6095.4
1108.104
River Rch & RM=ToneyFk1,Main      ,6095.4
789.7493
River Rch & RM=ToneyFk1,Main      ,5798.7
1291.956
River Rch & RM=ToneyFk1,Main      ,5798.7
942.5243
River Rch & RM=ToneyFk1,Main      ,4610.3
1329.260
River Rch & RM=ToneyFk1,Main      ,4610.3
975.1268
River Rch & RM=ToneyFk1,Main      ,217.6
1451.822
River Rch & RM=ToneyFk1,Main      ,217.6
1080.093
Boundary for River Rch & Prof#=ToneyFk1,Main      ,1
Up Type=0
Dn Type=3
Dn Slope=0.006605

--- ToneyFk1.g01 (geometry) ---

Geom Title=USGS 10m DEM
Program Version=4.00

River Reach=ToneyFk1        ,Main
Reach XY= 30
     1768199.325      277770.821     1767670.325      277502.643
     1767474.712      277155.515     1767185.865      277123.733
     1766872.714      276843.299     1766523.107      276699.343
     1766450.194      276409.561     1765995.892      275995.454
     1765648.959       275446.73     1765400.438      275289.696
     1764816.201      274654.981     1764367.507      274015.592
     1763904.791      273552.876     1763392.532      273319.182
     1763229.881      273027.531     1762451.041      272745.734
     1762114.421      272356.632     1761892.457      272228.203
      1761510.63      271805.278     1761195.548      271285.582
     1760507.403       270776.24     1760187.175      270273.671
     1759794.789      270089.741     1759358.026      269657.652
     1759378.591      269458.544     1759083.943       269108.53
     1758763.506      269040.698     1758474.659      268806.068
     1757900.705      268539.656     1757835.365      267816.633

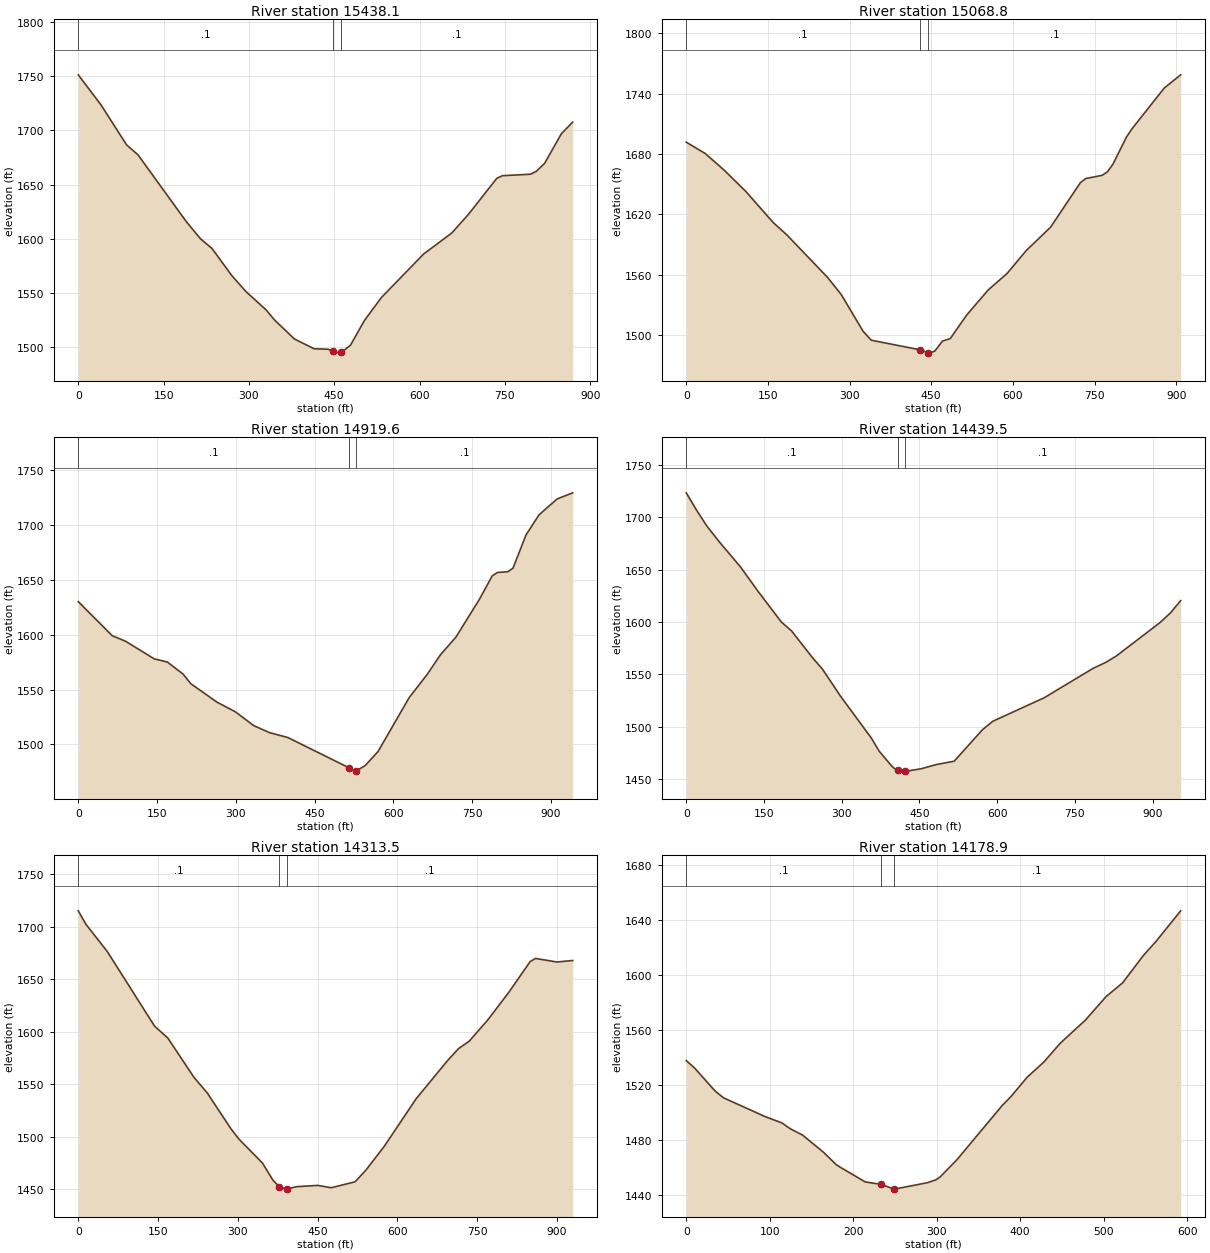
Type RM Length L Ch R = 1 ,15438.1 ,376.4,369.4,362.3
XS GIS Cut Line= 4
     1768443.875      277386.997     1768212.907      277719.663
      1768167.77      277801.256      1768032.36      278146.724
#Sta/Elev= 30
       0 1751.26      40 1723.54      85  1686.7     105 1677.54     190 1615.96
     215 1600.12     235 1591.32     270 1566.22     295 1551.45     330  1534.8
     345 1525.41     380 1507.86   414.8  1498.8   439.3 1498.38   447.7 1496.56
     459 1494.81   462.7 1495.54   478.6 1502.13   503.2 1524.95   532.9 1546.02
   607.1 1586.12   656.6 1605.46   686.2 1622.83   735.7  1655.8   745.6  1658.3
   795.1 1659.68     805 1662.26   819.8 1669.61   849.5  1697.1   869.3 1707.68
#Mann= 3 , 0 , 0
       0      .1       0   447.7    .045       0   462.7      .1       0
Bank Sta=447.7,462.7
XS Rating Curve= 0 ,0
Exp/Cntr=0.3,0.1

Type RM Length L Ch R = 1 ,15068.8 ,144.2,149.1,154
XS GIS Cut Line= 4
     1768113.953      277217.953     1767879.591      277535.645
      1767862.23      277624.182      1767683.42      278007.842
#Sta/Elev= 30
       0 1691.65      35 1680.34      70  1663.7   109.9 1642.44   159.9 1611.69
   184.9  1599.5   259.9 1557.12   284.8 1540.24   324.8 1503.84   339.8 1494.92
   429.5 1485.35   444.5 1482.41     447 1482.05   456.5 1484.02   470.8 1494.04
     485 1496.48   514.9  1519.7   554.7  1544.8   589.6  1561.3   624.4 1583.88
   669.3 1607.17     724  1651.4     734 1655.54   763.9 1658.69   773.8 1662.26
   783.8 1669.71   808.7 1696.73   818.6 1704.77   878.4 1745.59   908.3 1758.56
#Mann= 3 , 0 , 0
       0      .1       0   429.5    .045       0   444.5      .1       0
Bank Sta=429.5,444.5
XS Rating Curve= 0 ,0
Exp/Cntr=0.3,0.1

Type RM Length L Ch R = 1 ,14919.6 ,481.5,480.2,478.3
XS GIS Cut Line= 4
     1768012.489      277109.498     1767744.181      277506.132
      1767709.46      277585.989     1767550.862      277926.537
#Sta/Elev= 30
       0 1630.19    64.8 1599.04    89.8 1594.13   144.7 1577.95   169.6  1575.1
   199.5 1564.14   214.5 1555.27   264.4 1538.43   299.3 1529.67   334.2  1517.1
   364.1 1510.72     399 1506.27   514.7 1478.86   527.2  1475.6   529.7 1475.82
   546.6 1480.76   570.9  1493.5   630.2 1542.66   664.8    1564   689.5 1581.57
   719.2 1597.81   763.7 1632.08   788.4 1653.72   798.3 1656.76     818 1657.42
   827.9 1660.68   852.6 1690.94   877.4 1709.29     912 1723.85   941.6 1729.39
#Mann= 3 , 0 , 0
       0      .1       0   514.7    .045       0   529.7      .1       0
Bank Sta=514.7,529.7
XS Rating Curve= 0 ,0
Exp/Cntr=0.3,0.1

Type RM Length L Ch R = 1 ,14439.5 ,125.7,126,128.4
XS GIS Cut Line= 4
       1767658.8      276784.104     1767485.514      277141.568
     1767456.001      277221.425     1767178.223      277603.083
#Sta/Elev= 30
       0  1723.3    19.9 1706.77    39.7 1691.71    64.6 1676.05   104.3 1652.88
     139 1629.04   183.7 1599.97   203.6 1591.35   243.3  1566.2   263.2 1554.89
   297.9 1529.16   357.5 1489.12   372.4  1476.7   397.2 1462.23     402 1460.16
   408.2  1459.1   423.2  1457.7   425.6 1457.69     454 1460.01   482.4 1463.93
   517.2 1467.16   571.8 1497.21   591.7 1505.26   691.1 1527.76   785.5 1555.83
   810.3  1561.6   830.2 1567.59   914.7 1599.55   934.6 1608.66   954.4 1620.45
#Mann= 3 , 0 , 0
       0      .1       0   408.2    .045       0   423.2      .1       0
Bank Sta=408.2,423.2
XS Rating Curve= 0 ,0
Exp/Cntr=0.3,0.1

Type RM Length L Ch R = 1 ,14313.5 ,142.7,134.6,124.9
XS GIS Cut Line= 4
     1767492.458      276750.963     1767365.728      277105.112
      1767334.48      277172.816     1766980.332      277495.716
#Sta/Elev= 30
       0 1715.14    14.8 1702.05    54.4 1676.52   143.5 1605.35   168.3 1594.08
   217.8 1556.46   242.5 1541.79     287 1507.73   301.9 1497.94   346.4    1475
   366.2 1458.66     378 1452.57     391 1450.13     393 1450.33   410.9 1452.49
   450.7 1453.68   475.7 1451.44   520.6 1457.09   540.6 1467.99   575.5 1490.86
   635.4 1536.12   695.3 1572.98   715.3 1583.94   735.3    1591   770.2  1611.2
   810.2 1637.84   850.1 1666.88   860.1 1669.81     900 1666.42     930 1667.81
#Mann= 3 , 0 , 0
       0      .1       0     378    .045       0     393      .1       0
Bank Sta=378,393
XS Rating Curve= 0 ,0
Exp/Cntr=0.3,0.1

Type RM Length L Ch R = 1 ,14178.9 ,244.1,260.6,277
XS GIS Cut Line= 3
      1767235.53      276883.687     1767226.965      277177.749
     1766987.148      277354.757
#Sta/Elev= 30
       0 1537.48      10 1532.08    34.9 1515.13    44.9 1510.33    94.7 1496.69
   114.7 1492.14   124.7 1487.88   139.6 1483.18   164.6  1470.7   179.5  1461.9
   184.5  1459.9   214.4 1449.25   233.6 1447.42   248.6 1444.09   249.3    1444
   289.2 1448.72   299.2 1450.82   304.1 1452.88     324 1465.24   378.6 1504.94
   388.6 1511.09   408.4 1525.44   428.3 1536.42   448.2 1550.27     478 1566.86
   502.8 1583.99   522.7 1594.03   547.5  1613.9   562.4 1623.98   592.2 1646.39
#Mann= 3 , 0 , 0
       0      .1       0   233.6    .045       0   248.6      .1       0
Bank Sta=233.6,248.6
XS Rating Curve= 0 ,0
Exp/Cntr=0.3,0.1

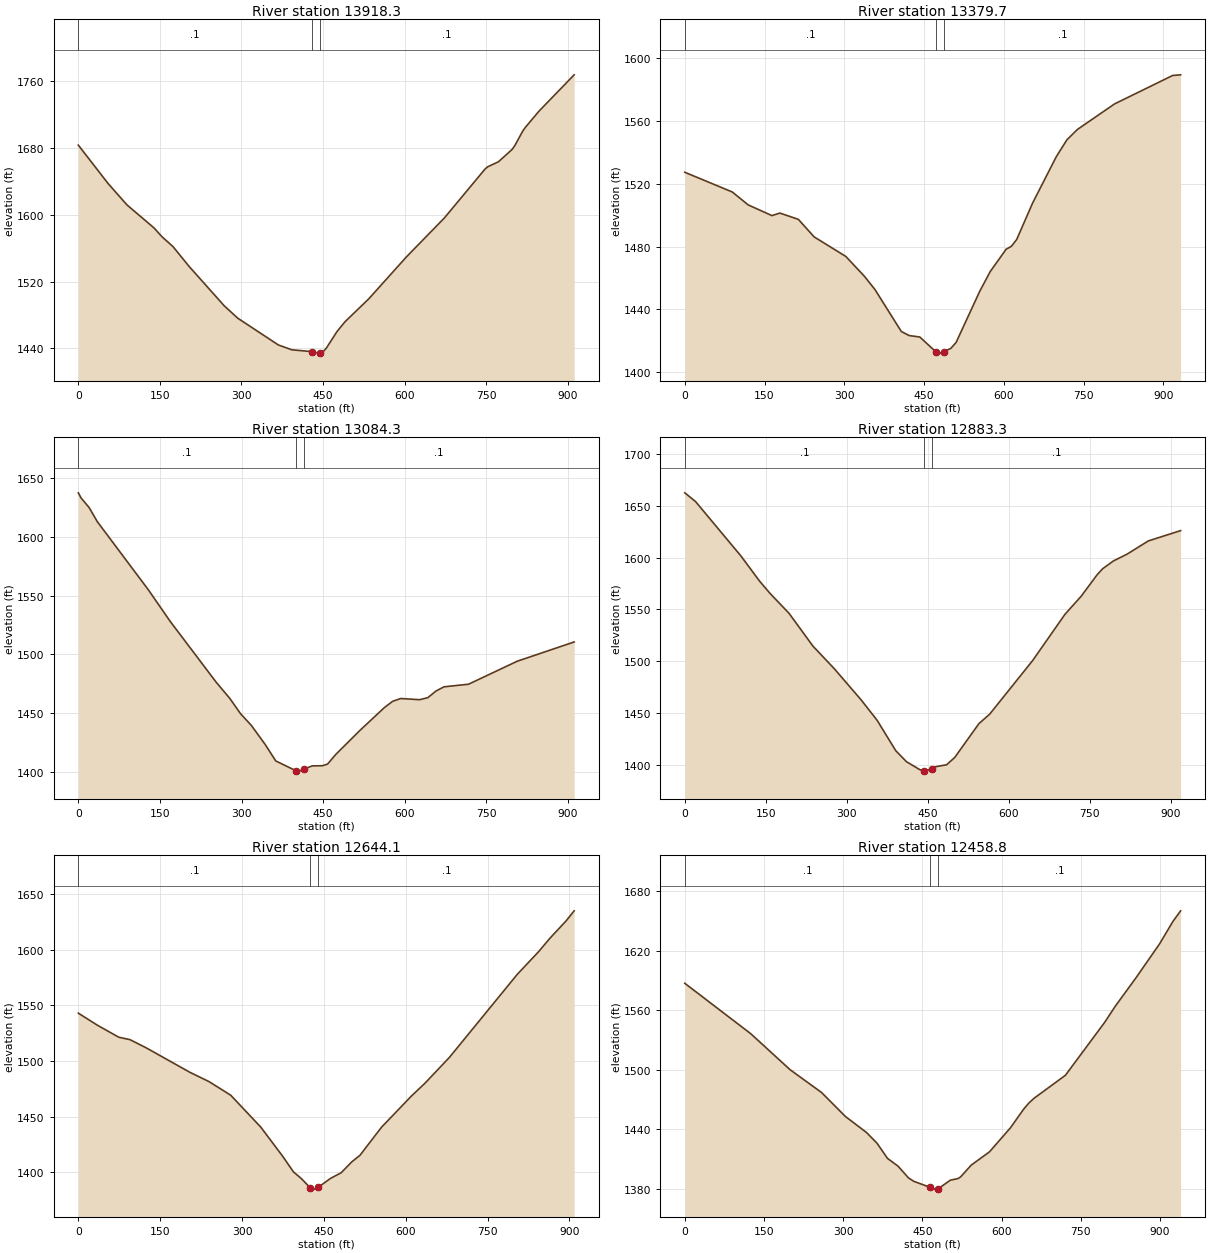
Type RM Length L Ch R = 1 ,13918.3 ,540.6,538.6,536.6
XS GIS Cut Line= 4
     1767264.781      276641.977     1767035.884      276973.174
     1766933.459      277084.279     1766733.353      277381.285
#Sta/Elev= 30
       0 1683.15    54.7 1637.26    89.5 1611.62   139.2 1584.13   154.1  1573.4
     174 1561.85   203.8 1538.02   268.4 1490.92   293.2 1476.16   367.8 1444.18
   392.7 1438.35     429 1436.23   441.6 1434.39     444 1434.83   451.3  1436.8
   456.2  1440.5   475.7 1460.21   490.3 1471.85   534.2 1499.38   603.4 1549.51
   673.1    1596   747.7 1654.36   752.7 1657.18   772.6 1663.25   797.4 1677.83
   802.4 1682.22   817.3 1700.01   822.3 1704.53   847.2 1723.82   911.8 1767.21
#Mann= 3 , 0 , 0
       0      .1       0     429    .045       0     444      .1       0
Bank Sta=429,444
XS Rating Curve= 0 ,0
Exp/Cntr=0.3,0.1

Type RM Length L Ch R = 1 ,13379.7 ,276.3,295.4,314.6
XS GIS Cut Line= 4
     1766941.043      276432.119     1766596.671      276709.299
     1766539.382      276782.212      1766285.36      277088.534
#Sta/Elev= 30
       0  1527.4    89.4 1514.82   119.2 1506.61   163.9 1499.78   178.8 1501.39
   213.6 1497.41   243.4 1486.19     303 1473.72   337.8 1461.14   357.6 1452.72
   407.3 1425.91   422.2 1423.31   442.1 1422.41   472.9 1412.76   481.1 1412.12
   487.9  1413.1   500.6  1415.2   510.4 1418.95   554.7 1451.46   574.6 1464.13
   604.4 1478.32   614.4 1480.22   624.3 1484.52   654.2 1507.72   698.9 1537.38
   718.8 1548.07   738.7 1554.72   808.4 1570.96   917.8 1589.11   932.7 1589.51
#Mann= 3 , 0 , 0
       0      .1       0   472.9    .045       0   487.9      .1       0
Bank Sta=472.9,487.9
XS Rating Curve= 0 ,0
Exp/Cntr=0.3,0.1

Type RM Length L Ch R = 1 ,13084.3 ,218.1,201,186.2
XS GIS Cut Line= 4
     1766751.177      276198.909     1766506.398      276480.144
     1766421.333      276485.352     1766091.489        276796.1
#Sta/Elev= 30
       0 1637.22       5  1632.9    19.9  1624.7    34.8 1612.82   129.2 1554.58
     169    1528   253.5 1476.38   278.4 1462.72   298.3 1449.63   318.2 1439.66
     343 1423.87   362.9 1409.63   399.5 1401.43     406    1401   414.5 1402.68
   429.7 1405.44   448.6 1405.58   458.1    1407     473 1415.13   517.8 1435.68
   562.6    1455   577.6 1460.26   592.5 1462.63   627.4 1461.64   642.3 1463.35
   657.3 1469.01   672.2 1472.58     717 1474.75   806.7  1494.3   911.2 1510.64
#Mann= 3 , 0 , 0
       0      .1       0   399.5    .045       0   414.5      .1       0
Bank Sta=399.5,414.5
XS Rating Curve= 0 ,0
Exp/Cntr=0.3,0.1

Type RM Length L Ch R = 1 ,12883.3 ,237.2,239.2,240.8
XS GIS Cut Line= 3
     1766645.189      276019.139      1766339.22      276356.218
      1765993.93      276665.263
#Sta/Elev= 30
       0 1662.46    19.8 1654.12   103.9 1601.65   138.6 1577.28   158.3 1565.26
     193 1546.36   237.5  1514.6   277.1 1492.79   326.6 1462.85   356.3 1443.14
   390.9 1413.78   410.7 1403.17   435.4 1395.52   443.3 1394.27   445.3 1394.09
   458.3 1396.59   465.2 1398.38   485.1 1400.25   500.1 1407.27   544.9 1439.87
   564.9 1449.06   644.6 1500.83   704.4 1545.36   734.3 1562.69   764.2 1583.65
   774.1 1589.23   794.1 1596.77     819  1603.2   858.8 1616.08   918.6 1626.02
#Mann= 3 , 0 , 0
       0      .1       0   443.3    .045       0   458.3      .1       0
Bank Sta=443.3,458.3
XS Rating Curve= 0 ,0
Exp/Cntr=0.3,0.1

Type RM Length L Ch R = 1 ,12644.1 ,184.1,185.3,186.4
XS GIS Cut Line= 4
      1766501.19      275874.273     1766219.954        276150.3
     1766140.098      276221.477     1765775.533      276403.759
#Sta/Elev= 30
       0 1542.93    34.9 1532.12    69.8  1522.5    74.8 1521.23    94.8 1519.12
   124.7  1511.7   204.5 1489.79   239.4 1481.48   279.3 1469.22   334.2 1440.67
   374.1 1414.67   394.1 1400.46   408.6 1394.41   424.9 1386.15   428.1 1385.15
     433  1384.9   439.9 1386.67   462.1 1394.52   481.6 1399.59     501 1409.33
     516 1415.23   555.7 1440.54   610.4 1468.52   635.2    1480     680  1503.2
   804.2 1577.68     844 1598.43   863.9 1610.04   893.7  1625.7   908.6 1634.82
#Mann= 3 , 0 , 0
       0      .1       0   424.9    .045       0   439.9      .1       0
Bank Sta=424.9,439.9
XS Rating Curve= 0 ,0
Exp/Cntr=0.3,0.1

Type RM Length L Ch R = 1 ,12458.8 ,124.2,122.9,121.7
XS GIS Cut Line= 4
     1766343.212      275669.422     1766082.809      276028.779
     1766002.952      276094.747     1765643.037      276249.618
#Sta/Elev= 30
       0 1587.09   124.7  1536.4   199.4 1500.08   259.3 1476.96   304.2 1452.94
   344.1 1436.83     364 1426.07     384 1410.68   403.9 1402.89   423.8 1391.02
   433.8 1387.58   465.3 1381.43   473.4 1379.73   480.3 1380.26     503 1388.73
   517.8 1390.41   522.7 1392.18   542.4 1403.84   577.1 1417.27   616.8 1441.47
   641.6  1460.1   651.5 1466.33   661.4 1471.19     721 1494.42   795.4 1547.79
   815.2 1563.82   854.9 1592.81   899.5 1626.92   924.3 1649.15   939.2 1660.09
#Mann= 3 , 0 , 0
       0      .1       0   465.3    .045       0   480.3      .1       0
Bank Sta=465.3,480.3
XS Rating Curve= 0 ,0
Exp/Cntr=0.3,0.1

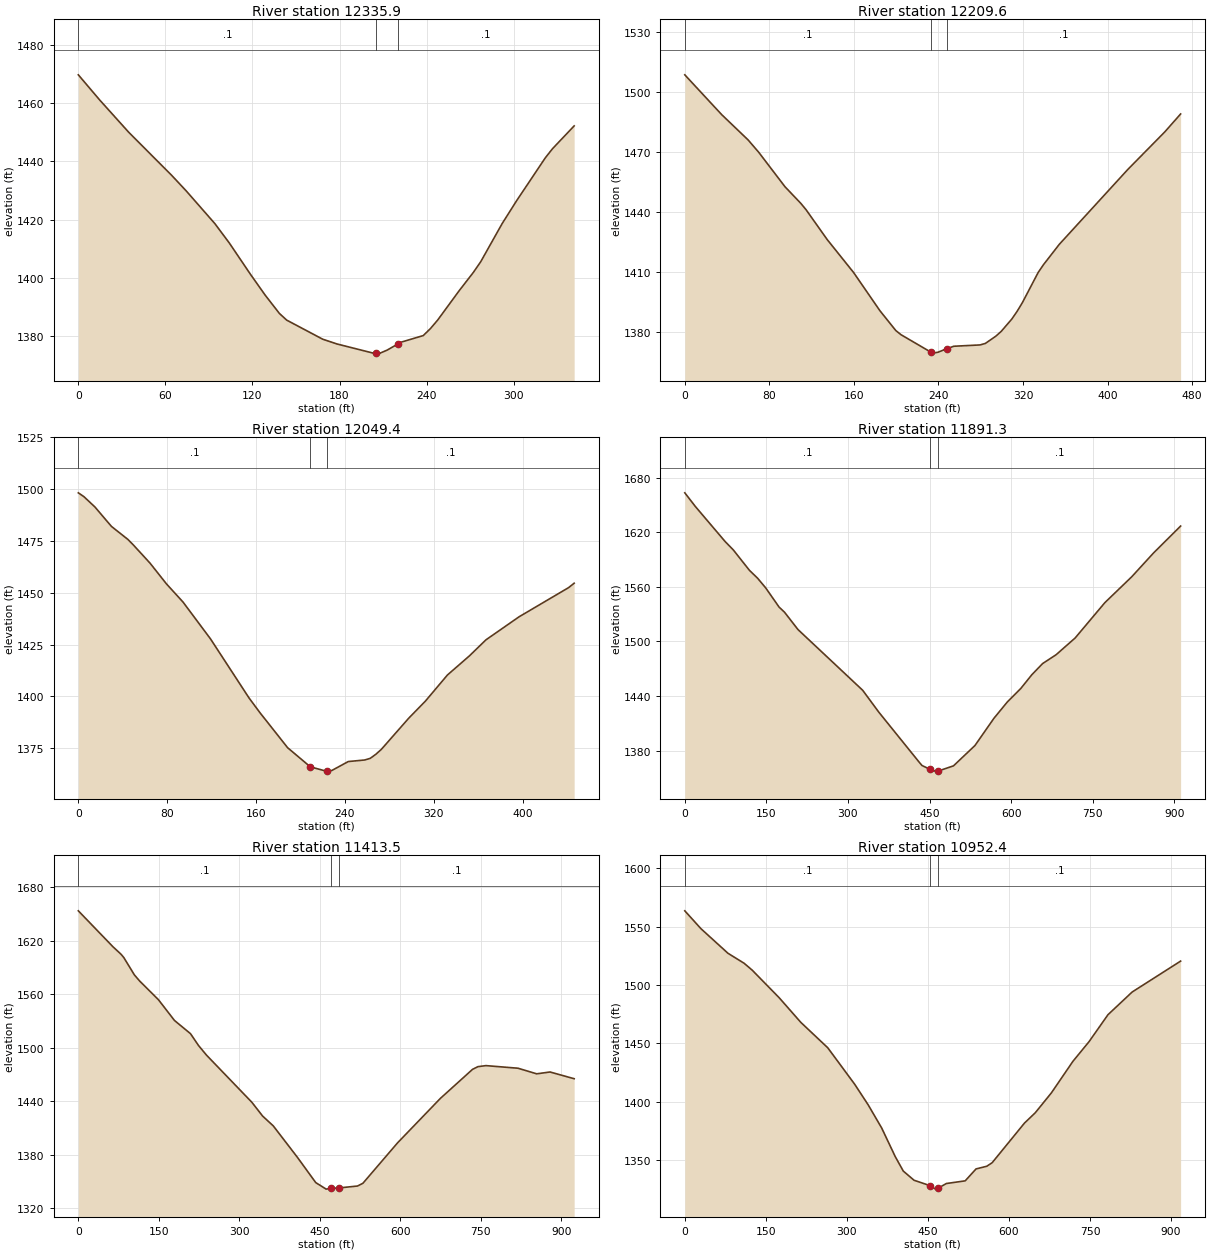
Type RM Length L Ch R = 1 ,12335.9 ,125.4,126.3,126.4
XS GIS Cut Line= 2
     1766130.657      275821.638     1765876.564      276050.036
#Sta/Elev= 30
       0 1469.77    14.8 1461.08    34.7 1450.05    64.4 1435.19    74.3 1429.91
    94.1 1418.64     104 1412.02   118.8  1401.1   128.7 1394.11   138.6 1387.76
   143.6 1385.48   168.4 1378.93   178.3 1377.28     203 1374.17   205.4 1374.15
     208 1374.14   212.9  1375.2   220.4 1377.34   222.8 1377.96   237.7 1380.17
   242.6 1382.54   247.6 1385.47   262.4 1395.55   272.3 1401.92   277.3 1405.54
   292.1 1418.67     302 1426.48   321.8 1441.23   326.8 1444.39   341.7 1452.22
#Mann= 3 , 0 , 0
       0      .1       0   205.4    .045       0   220.4      .1       0
Bank Sta=205.4,220.4
XS Rating Curve= 0 ,0
Exp/Cntr=0.3,0.1

Type RM Length L Ch R = 1 ,12209.6 ,161.9,160.3,159.2
XS GIS Cut Line= 2
     1766136.367       275690.31      1765770.93      275984.371
#Sta/Elev= 30
       0 1508.54    34.9 1488.68    59.9 1476.05    69.9 1469.92    94.8 1452.69
   109.8 1444.38   114.8 1441.18   134.7 1426.35   159.7 1409.89   184.6 1390.83
   199.6 1380.95   204.6 1378.84   232.7 1370.19   234.5 1369.66   239.5 1370.09
   247.7 1371.83   254.5 1373.09   279.4 1373.75   284.4 1374.51   294.4 1378.17
   299.4 1380.53   309.4 1386.67   314.4  1390.5   319.4 1394.87   334.3 1409.88
   339.3 1413.76   354.3 1423.94   419.2 1461.35   454.1 1480.04   469.1 1489.01
#Mann= 3 , 0 , 0
       0      .1       0   232.7    .045       0   247.7      .1       0
Bank Sta=232.7,247.7
XS Rating Curve= 0 ,0
Exp/Cntr=0.3,0.1

Type RM Length L Ch R = 1 ,12049.4 ,158.9,158.1,157.3
XS GIS Cut Line= 2
     1766027.878      275553.271     1765705.266      275861.608
#Sta/Elev= 30
       0  1498.2       5 1496.36    14.9  1491.4    29.8 1482.01    44.6 1475.74
    49.6 1473.02    64.5 1464.32    79.3  1454.3    94.2 1445.55     119 1427.74
   153.7 1399.24   163.6 1392.09   188.4 1375.28   208.9 1366.03   223.1 1363.99
   223.9 1364.04   228.1 1364.28     243 1368.61   257.8 1369.36   262.8 1370.17
   267.8 1372.12   272.7 1374.46   297.5 1389.57   312.4 1397.75   332.2 1410.33
     352 1419.56   366.9  1427.3   396.7 1438.41   441.3 1452.48   446.3 1454.61
#Mann= 3 , 0 , 0
       0      .1       0   208.9    .045       0   223.9      .1       0
Bank Sta=208.9,223.9
XS Rating Curve= 0 ,0
Exp/Cntr=0.3,0.1

Type RM Length L Ch R = 1 ,11891.3 ,479.1,477.7,484.6
XS GIS Cut Line= 4
     1766094.805      275271.439     1765779.005      275572.205
     1765732.133      275620.814     1765407.687      275868.083
#Sta/Elev= 30
       0  1663.4    19.8  1648.1    74.3 1609.74    89.2 1600.62   118.9 1578.16
   133.8 1569.54   148.7 1558.91   173.4 1537.74   183.4 1532.09   208.1 1513.07
   327.1 1446.26   356.8 1422.16   431.2 1367.03   436.1 1363.61   451.1 1359.26
   460.2 1357.39   466.1 1357.53     494 1363.19   533.5 1385.57   568.3 1415.44
   593.2 1433.58     618 1448.44     638 1463.34   657.8 1475.63   682.7 1485.39
   717.6 1503.74   772.3 1542.63     822 1571.26   861.8 1597.27   911.6 1626.86
#Mann= 3 , 0 , 0
       0      .1       0   451.1    .045       0   466.1      .1       0
Bank Sta=451.1,466.1
XS Rating Curve= 0 ,0
Exp/Cntr=0.3,0.1

Type RM Length L Ch R = 1 ,11413.5 ,460.5,461.1,461.8
XS GIS Cut Line= 4
     1765744.624      274955.501     1765440.481      275249.305
     1765383.192      275315.274     1765015.731      275504.732
#Sta/Elev= 30
       0 1653.63    64.7 1613.22    79.6 1604.92    84.6 1601.33   104.5 1581.74
   114.4 1574.82   149.2 1554.01   179.1  1530.7     209 1515.85   223.9 1502.62
   238.8  1491.8   323.4 1438.88   343.3 1423.51   363.2 1412.46     408 1377.33
   442.3 1348.88   461.7 1341.56   471.5 1342.57   486.5 1342.94   520.2 1345.06
   530.2 1348.15   594.9 1393.57   674.6 1443.37   734.4 1475.88   744.4 1478.88
   759.3 1480.06   819.1 1477.13   853.9 1470.86   878.8  1472.9   923.7 1465.37
#Mann= 3 , 0 , 0
       0      .1       0   471.5    .045       0   486.5      .1       0
Bank Sta=471.5,486.5
XS Rating Curve= 0 ,0
Exp/Cntr=0.3,0.1

Type RM Length L Ch R = 1 ,10952.4 ,185.7,183.6,181.3
XS GIS Cut Line= 3
     1765381.449        274550.5     1765154.038      274896.893
     1764812.404      275266.542
#Sta/Elev= 30
       0 1563.64      30 1548.27    79.9 1527.23   109.8 1518.65   124.8 1512.72
   174.7 1489.07   214.7 1467.96   264.6 1446.15   314.5 1414.81   339.5 1397.12
   364.4 1377.31   389.4 1352.86   404.4 1340.35   424.3 1332.48   454.1 1327.81
   464.2 1324.86   469.1 1325.72   484.1 1329.67     519 1331.96     539 1342.18
   558.9 1344.48   568.9 1347.54   628.7 1381.52   648.6 1390.34   678.5 1407.44
   718.4 1434.53   748.3 1451.44   783.2 1474.49     828 1493.98   917.7  1520.5
#Mann= 3 , 0 , 0
       0      .1       0   454.1    .045       0   469.1      .1       0
Bank Sta=454.1,469.1
XS Rating Curve= 0 ,0
Exp/Cntr=0.3,0.1

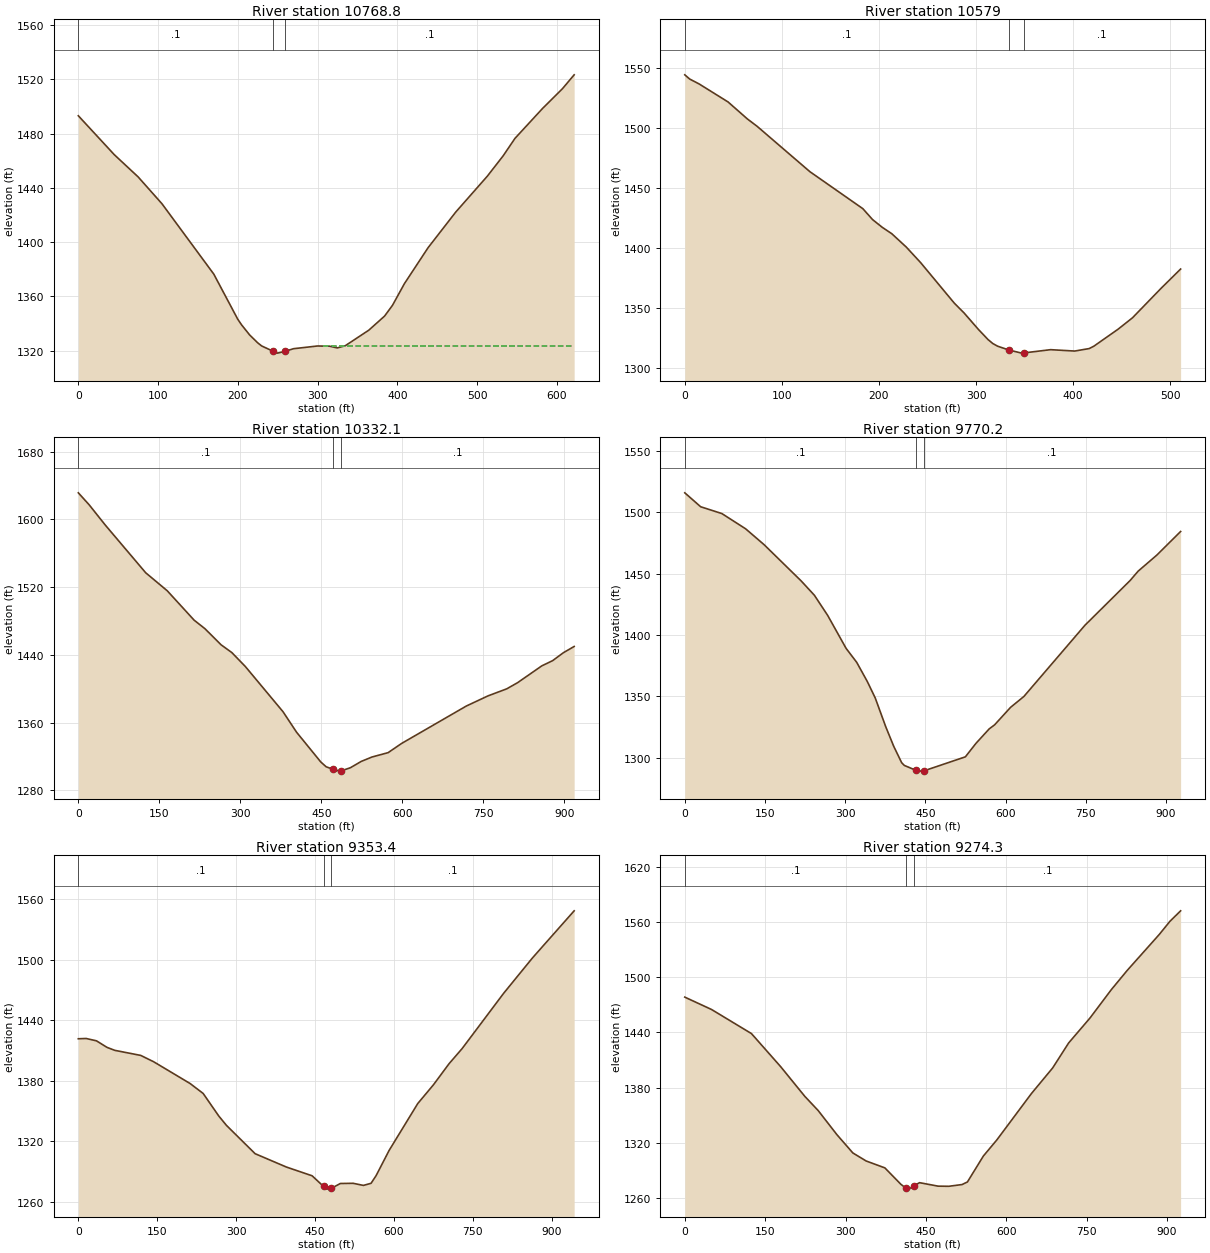
Type RM Length L Ch R = 1 ,10768.8 ,188.8,189.8,190.8
XS GIS Cut Line= 3
     1765139.982      274619.696     1764945.844      274873.788
     1764765.981      275116.461
#Sta/Elev= 30
       0 1493.14      45 1464.52      75 1448.08   104.9 1428.29   169.9 1376.43
   199.9 1343.24   204.8    1339   214.8 1331.65   224.8  1325.9   229.8 1323.54
     244 1319.67   249.8 1318.22     259 1319.51   269.8 1321.47   299.8 1323.47
   314.8 1323.36   324.7 1322.07   334.6  1323.6   364.3 1335.14   384.1 1345.55
     394 1353.47   408.9 1369.39   438.6  1395.9   473.3 1422.17   512.9 1448.61
   532.7 1463.56   547.6 1476.49   582.2 1498.54     607 1513.01   621.8 1523.31
#Mann= 3 , 0 , 0
       0      .1       0     244    .045       0     259      .1       0
#XS Ineff= 2 , 0
                          306.67         1323.63
Permanent Ineff=
       F       F
Bank Sta=244,259
XS Rating Curve= 0 ,0
Exp/Cntr=0.3,0.1

Type RM Length L Ch R = 1 ,10579   ,244.5,246.9,249.3
XS GIS Cut Line= 2
     1765071.463      274425.558     1764743.141      274816.689
#Sta/Elev= 30
       0 1544.25       5 1540.76    14.9 1536.59    44.6 1521.63    64.4 1507.54
    74.4 1501.42   128.9 1463.54   183.4 1432.74   193.4 1423.67   203.3 1417.26
   213.2 1411.89   228.1 1400.78   242.9 1387.82   277.6 1354.04   287.6 1345.92
   302.4 1332.18   312.4 1323.66   317.3 1320.37   322.3 1318.16   333.9 1314.99
     347 1312.41   348.9 1312.55   376.8 1315.29   401.6 1314.14   416.5  1316.2
   421.4 1318.22   446.2 1332.29   461.1 1341.82   490.8 1366.59   510.7 1382.46
#Mann= 3 , 0 , 0
       0      .1       0   333.9    .045       0   348.9      .1       0
Bank Sta=333.9,348.9
XS Rating Curve= 0 ,0
Exp/Cntr=0.3,0.1

Type RM Length L Ch R = 1 ,10332.1 ,560.5,561.9,559.9
XS GIS Cut Line= 3
     1765097.617      274225.458     1764782.529      274417.751
     1764383.348      274794.956
#Sta/Elev= 30
       0 1631.35      20 1617.26    49.9 1593.31   124.7 1537.01   164.6 1515.77
   214.5    1481   234.4    1471   264.4 1451.92   284.3 1442.76   309.3 1426.31
   379.1 1372.92   404.1 1348.81     449 1313.63     459 1307.92   471.6 1305.01
     484 1302.79   486.6 1303.06   503.9  1306.8   523.9 1314.24   543.9 1319.46
   573.8 1324.62   598.8  1335.5   718.6 1379.64   758.6 1391.59   793.5 1399.96
   813.5 1407.19   858.4 1427.07   878.4  1433.2   898.4 1442.61   918.3 1449.96
#Mann= 3 , 0 , 0
       0      .1       0   471.6    .045       0   486.6      .1       0
Bank Sta=471.6,486.6
XS Rating Curve= 0 ,0
Exp/Cntr=0.3,0.1

Type RM Length L Ch R = 1 ,9770.2  ,418.5,416.8,418.4
XS GIS Cut Line= 3
     1764784.094      273853.159     1764402.341      274041.035
     1764070.499      274417.874
#Sta/Elev= 30
       0 1515.98    29.7 1504.62    69.3 1499.08   113.8 1486.64   148.4 1473.69
   217.7 1444.14   242.4 1432.48   267.2  1416.1   301.8 1389.12   321.6 1377.76
   341.4 1362.15   356.2 1348.79     376 1325.16   390.8 1309.34   405.7 1295.91
   410.6 1293.71   432.1 1289.75   440.4 1289.03   447.1 1289.21   524.9 1300.68
   544.8 1311.72   569.6 1323.52   579.6 1326.77   609.4 1341.01   634.3 1349.87
   748.6 1407.98   833.1 1444.46   848.1 1452.09   882.9 1465.12   927.6 1484.45
#Mann= 3 , 0 , 0
       0      .1       0   432.1    .045       0   447.1      .1       0
Bank Sta=432.1,447.1
XS Rating Curve= 0 ,0
Exp/Cntr=0.3,0.1

Type RM Length L Ch R = 1 ,9353.4  ,78.7,79.1,86.2
XS GIS Cut Line= 4
     1764413.585      273464.983     1764119.369      273751.119
     1763996.112      273869.169     1763781.206      274160.202
#Sta/Elev= 30
       0 1421.54    14.8 1421.83    34.6 1419.49    54.4 1413.06    69.2 1410.09
   118.7 1405.05   143.4 1398.73   212.6  1377.2   237.4 1367.36     267 1345.07
   281.8 1335.68   336.2 1307.68   395.6 1294.48   444.6 1285.79   466.3 1275.27
   473.8 1272.58   481.3 1273.39   498.2 1278.15   522.6 1278.35   542.1 1276.27
   556.7 1278.36   566.4 1286.06     591  1310.9   645.5 1357.38   675.2 1375.86
     705 1396.83   729.8 1411.78     809 1466.72   863.6 1501.62   942.9  1548.3
#Mann= 3 , 0 , 0
       0      .1       0   466.3    .045       0   481.3      .1       0
Bank Sta=466.3,481.3
XS Rating Curve= 0 ,0
Exp/Cntr=0.3,0.1

Type RM Length L Ch R = 1 ,9274.3  ,302.4,293.9,278.9
XS GIS Cut Line= 4
     1764321.417      273416.266     1764043.826      273722.233
     1763950.062      273767.881     1763584.876       273949.24
#Sta/Elev= 30
       0 1478.46    49.8 1465.05   124.4  1438.8   179.2 1402.61     224  1370.5
   248.9 1355.08   283.7 1328.97   313.6 1308.97   338.5  1300.2   373.3 1292.74
   403.2  1274.9   412.8 1270.57   418.1 1269.62   427.8 1273.32     438 1276.64
   472.7 1272.86   492.6  1272.7   517.4  1274.6   527.4 1277.43   557.2 1305.68
     582 1322.93   646.7  1373.5   686.5 1401.48   716.3 1428.64   756.1 1455.75
   795.9  1486.6   825.7 1507.63   885.4 1546.64   905.3 1560.96   925.2 1572.33
#Mann= 3 , 0 , 0
       0      .1       0   412.8    .045       0   427.8      .1       0
Bank Sta=412.8,427.8
XS Rating Curve= 0 ,0
Exp/Cntr=0.3,0.1

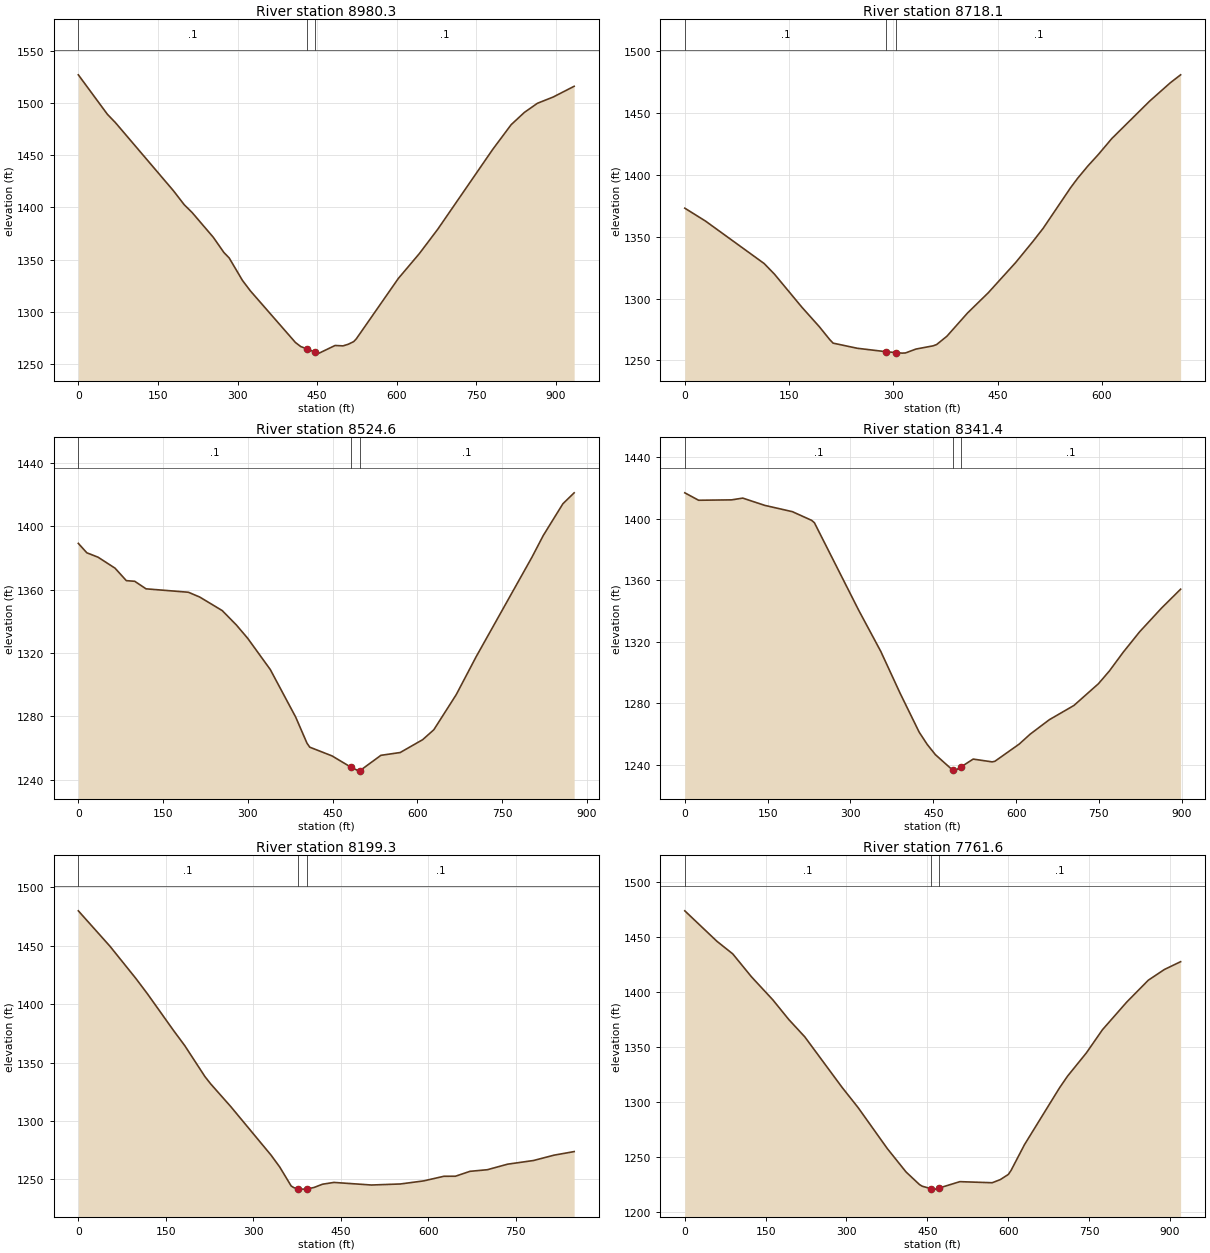
Type RM Length L Ch R = 1 ,8980.3  ,264.4,262.2,259.9
XS GIS Cut Line= 3
     1764032.255      273118.543     1763798.205      273603.557
     1763486.842      273847.566
#Sta/Elev= 30
       0 1526.95    54.8 1489.16    69.8 1481.26   179.5 1415.84   199.5 1402.65
   214.4 1395.18   254.3 1371.47   274.2 1356.98   284.2 1351.71   309.2 1330.23
   324.1 1320.23   408.9 1270.88   418.9 1266.97   431.1 1264.59   446.1 1261.62
   453.8 1260.65   483.7 1267.97   498.6 1267.59   508.6 1269.16   518.6 1271.61
   523.6 1274.25   602.8 1332.05   642.4 1355.86     677  1379.1   780.8 1455.68
   815.4 1479.24   840.2 1490.93   864.9 1499.72   894.6 1505.71   934.1 1515.99
#Mann= 3 , 0 , 0
       0      .1       0   431.1    .045       0   446.1      .1       0
Bank Sta=431.1,446.1
XS Rating Curve= 0 ,0
Exp/Cntr=0.3,0.1

Type RM Length L Ch R = 1 ,8718.1  ,197.5,193.6,189.7
XS GIS Cut Line= 3
     1763718.207      273115.127     1763604.008      273469.143
     1763458.405       273777.48
#Sta/Elev= 30
       0 1373.11    29.8 1362.67   114.1 1328.36     129 1319.73   168.6  1292.9
   193.4 1277.33   208.3 1266.96   213.3    1264     248 1259.86     289  1257.1
     304 1256.34   312.5 1255.93   317.4 1256.08   332.3  1259.2   357.1 1261.82
   362.1 1262.86   376.9 1269.57   406.6 1288.38   436.2 1304.61   475.8 1329.17
   500.5 1346.14   515.3 1356.81   554.8 1389.67   564.7 1397.12   579.5 1407.14
   594.4 1416.32   614.1 1429.42   668.5 1459.66   698.1 1474.44     713  1480.9
#Mann= 3 , 0 , 0
       0      .1       0     289    .045       0     304      .1       0
Bank Sta=289,304
XS Rating Curve= 0 ,0
Exp/Cntr=0.3,0.1

Type RM Length L Ch R = 1 ,8524.6  ,160.7,183.1,205.6
XS GIS Cut Line= 4
     1763718.348      272929.981     1763461.417      273280.658
     1763438.849      273398.707      1763211.43      273627.862
#Sta/Elev= 30
       0 1389.13      15  1383.2      35  1380.4      65 1373.48      85 1365.62
    99.9 1365.21   119.9 1360.45   194.9 1358.29   214.9 1355.27   254.8 1346.71
   279.8 1337.64   299.8 1329.25   339.8 1309.54   384.8 1279.52   404.8 1263.06
   409.7 1260.53   449.2 1255.02   482.8 1247.86   497.2 1245.42   497.8 1245.52
   535.7 1255.39   569.8 1257.16   609.6 1265.26   629.4 1271.54   669.2 1293.78
   703.9 1317.36   803.3 1380.55   823.1 1394.09   857.9 1414.15   877.8 1421.03
#Mann= 3 , 0 , 0
       0      .1       0   482.8    .045       0   497.8      .1       0
Bank Sta=482.8,497.8
XS Rating Curve= 0 ,0
Exp/Cntr=0.3,0.1

Type RM Length L Ch R = 1 ,8341.4  ,146,142.1,138.2
XS GIS Cut Line= 4
     1763693.409       272882.86     1763405.865      273181.704
     1763239.918      273253.925     1763140.253      273539.325
#Sta/Elev= 30
       0 1416.88      25 1412.05    84.9  1412.3   104.9 1413.45   144.9 1408.71
   194.9 1404.62   229.8 1398.96   234.8 1397.38   314.8  1340.6   354.8 1313.83
   389.7 1286.69   424.5 1261.18   439.2 1253.14   453.8 1246.57   485.3 1236.45
   488.1 1235.84   500.3 1238.58   522.3 1243.67   556.6 1241.86   561.5 1242.22
   605.6 1253.41   625.4 1259.85   660.1 1269.26   704.7 1278.54   749.3 1292.74
   769.2 1301.09   793.9 1313.13   823.7 1326.46   863.3 1341.85     898  1354.2
#Mann= 3 , 0 , 0
       0      .1       0   485.3    .045       0   500.3      .1       0
Bank Sta=485.3,500.3
XS Rating Curve= 0 ,0
Exp/Cntr=0.3,0.1

Type RM Length L Ch R = 1 ,8199.3  ,453.1,437.7,422.4
XS GIS Cut Line= 4
     1763440.585      272745.963     1763305.175      273063.655
     1763223.582      273117.472     1763003.108      273459.468
#Sta/Elev= 30
       0    1480    54.3 1449.64    98.7 1422.05   118.4 1408.99   162.8 1377.82
   182.5 1364.53   217.1 1338.03   226.9 1331.81   261.5 1312.27   330.6 1270.67
   345.4 1260.54   364.9 1244.37   369.8 1242.89   376.4 1242.13   384.4  1241.7
   391.4 1241.81     404  1243.1   418.6 1245.91   438.2 1247.44   502.6 1245.22
   552.3 1246.12     592 1248.75   626.7  1252.7   646.5 1252.74   671.4 1256.94
   701.1 1258.31   735.9 1263.06   780.5 1266.22   815.3 1270.76     850 1273.85
#Mann= 3 , 0 , 0
       0      .1       0   376.4    .045       0   391.4      .1       0
Bank Sta=376.4,391.4
XS Rating Curve= 0 ,0
Exp/Cntr=0.3,0.1

Type RM Length L Ch R = 1 ,7761.6  ,408,407.1,406.3
XS GIS Cut Line= 3
     1763141.919      272521.932     1762902.419      272867.485
      1762749.35      273342.906
#Sta/Elev= 30
       0 1473.79    59.4 1446.17      89  1434.6   123.7 1413.76   163.2 1392.88
   192.9 1374.93   222.6 1359.15   291.8 1313.18   321.5 1294.82   375.9 1257.38
   410.5 1236.21   435.4 1224.77   440.4 1223.28   456.2 1221.08   465.4 1220.61
   471.2  1221.5   510.3 1227.41   570.3 1226.42   585.3 1229.26   600.2 1233.94
   605.2 1237.52   630.2 1261.06   695.1 1312.65   710.1 1323.38   745.1 1344.58
     775 1365.69     820 1390.82     860 1410.69   889.9 1420.46   919.9 1427.51
#Mann= 3 , 0 , 0
       0      .1       0   456.2    .045       0   471.2      .1       0
Bank Sta=456.2,471.2
XS Rating Curve= 0 ,0
Exp/Cntr=0.3,0.1