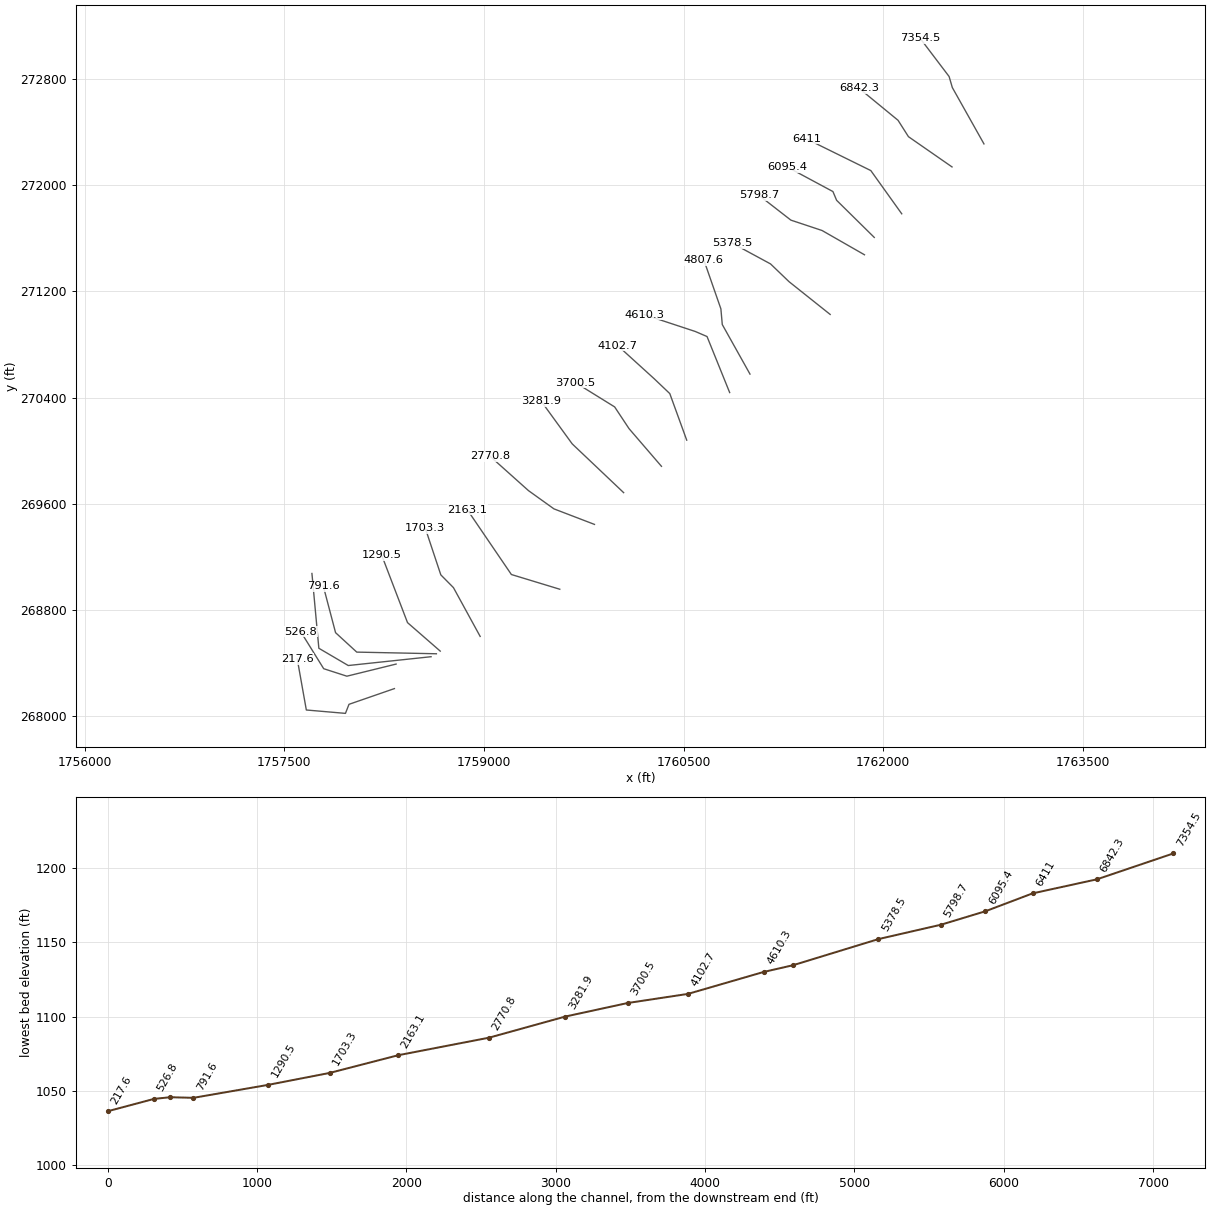
HEC-RAS study ToneyFk1.prj: ToneyFk1

--- ToneyFk1.g01 (geometry) --- (continued)

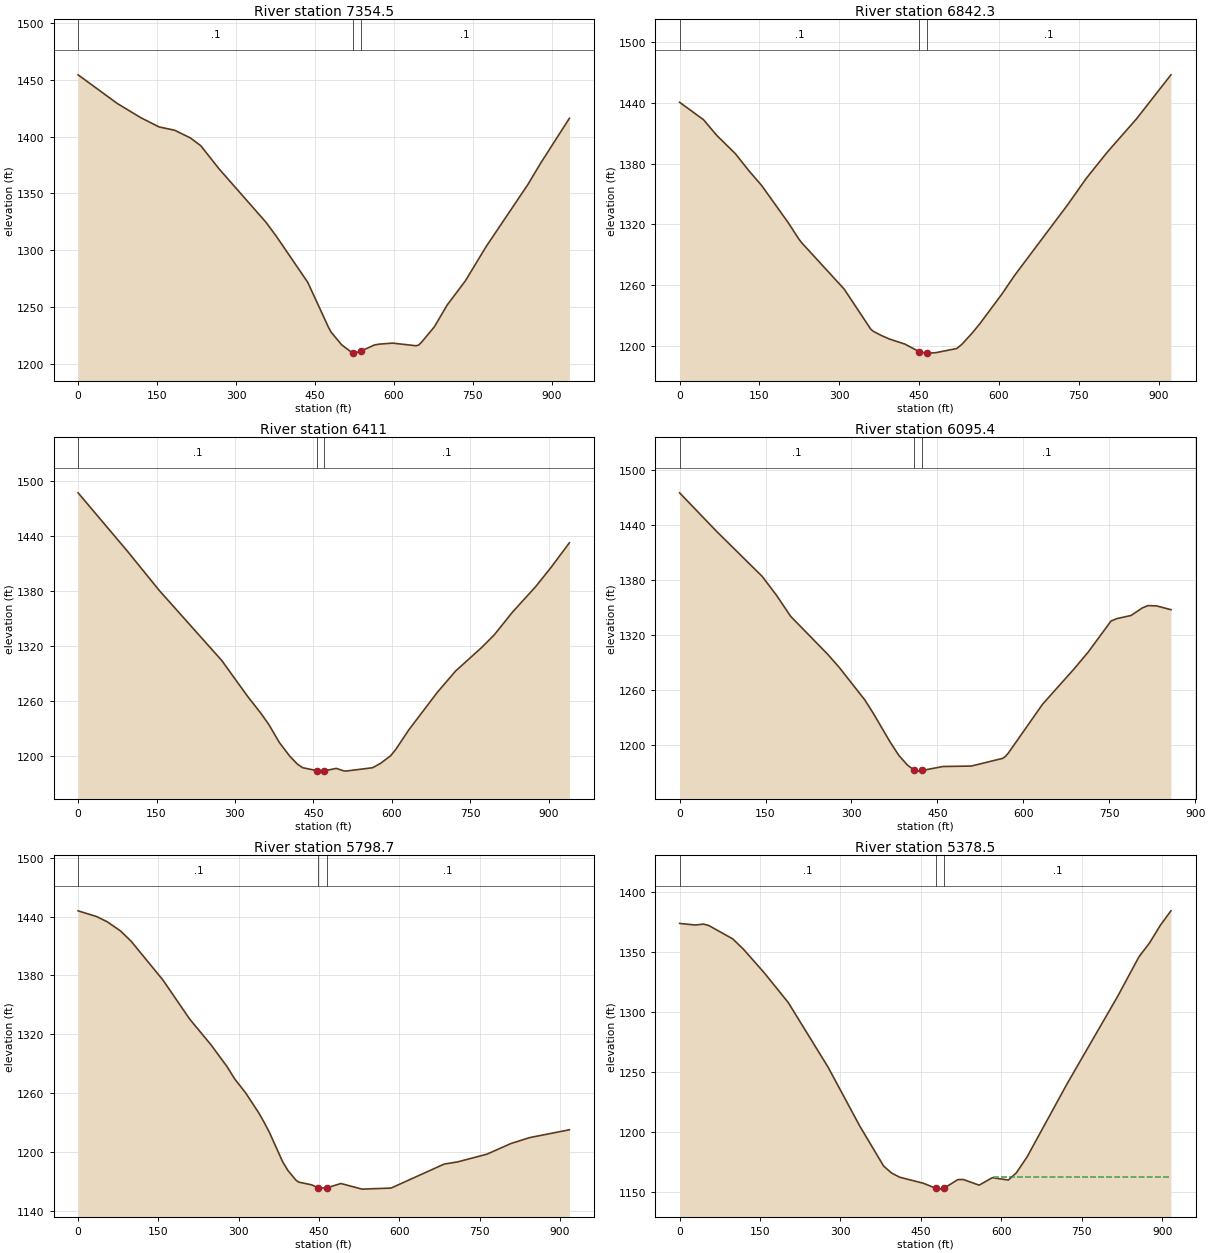
Type RM Length L Ch R = 1 ,7354.5  ,506,512.2,518.4
XS GIS Cut Line= 4
     1762758.106      272311.434     1762520.494      272735.547
      1762496.19      272818.876     1762278.552       273106.46
#Sta/Elev= 30
       0 1454.15    74.4 1429.02     119 1416.57   153.8 1408.44   183.5  1405.5
   213.3 1398.79   233.2 1391.88   267.9 1371.59   357.2 1324.64     377 1312.24
   436.5 1271.96   476.2 1232.15   481.2 1228.09   500.6 1217.29   521.6 1209.95
   524.7  1209.9   536.6 1211.55   563.3  1217.1   572.9 1217.82   597.6 1218.69
   642.1 1216.38     647 1216.94     652 1219.16   676.7 1232.83   701.4 1252.17
     736 1273.43   775.5 1303.52   854.6 1357.83   879.2 1376.83   933.6 1416.02
#Mann= 3 , 0 , 0
       0      .1       0   521.6    .045       0   536.6      .1       0
Bank Sta=521.6,536.6
XS Rating Curve= 0 ,0
Exp/Cntr=0.3,0.1

Type RM Length L Ch R = 1 ,6842.3  ,418.2,431.3,444.6
XS GIS Cut Line= 4
     1762518.154      272137.964      1762190.65      272365.774
     1762112.529      272489.032     1761820.613      272729.182
#Sta/Elev= 30
       0 1440.76    44.9 1423.51    69.8 1407.99   104.7  1389.9   129.7  1373.3
   154.6 1358.06   204.5 1321.22   224.4 1305.04   229.4  1301.7   309.2 1255.78
     359 1216.23     364 1214.01     379 1209.92     394 1206.44   423.3  1201.4
   450.3 1193.81   465.3 1192.51     467 1192.47   481.6 1192.95   520.6 1197.06
   530.3 1201.22   549.8 1212.46   564.8 1222.16   604.6 1250.34   629.4  1269.5
   728.9 1339.34   763.7 1365.33   803.5  1391.5   858.2 1424.33   922.9 1467.93
#Mann= 3 , 0 , 0
       0      .1       0   450.3    .045       0   465.3      .1       0
Bank Sta=450.3,465.3
XS Rating Curve= 0 ,0
Exp/Cntr=0.3,0.1

Type RM Length L Ch R = 1 ,6411    ,330.1,315.6,299
XS GIS Cut Line= 3
     1762140.051      271785.149     1761907.679      272110.579
     1761423.418      272349.605
#Sta/Elev= 30
       0 1487.34      95 1423.08     155 1380.75   274.9 1303.92   324.9 1264.28
   349.9 1246.07   364.9 1233.95   384.9  1214.4   404.8 1199.44   419.7 1190.53
   429.6 1186.75   456.2 1183.59   464.3    1183   471.2 1183.32     494    1186
   508.9 1183.13   513.8 1183.16   563.4 1186.72   578.2 1191.34   598.1 1199.92
     608 1206.99   632.7 1228.16   687.2 1269.17   721.9 1292.32   771.5 1317.93
   796.2 1332.06   830.9 1356.85   875.5 1384.87   905.2  1406.1   939.9 1432.75
#Mann= 3 , 0 , 0
       0      .1       0   456.2    .045       0   471.2      .1       0
Bank Sta=456.2,471.2
XS Rating Curve= 0 ,0
Exp/Cntr=0.3,0.1

Type RM Length L Ch R = 1 ,6095.4  ,279.2,296.7,316
XS GIS Cut Line= 4
     1761933.719      271607.133     1761650.747      271886.633
     1761622.971      271952.602     1761280.975       272136.62
#Sta/Elev= 30
       0 1474.66    64.6 1432.59   144.2 1383.47     169 1362.98   193.9 1339.87
   258.5  1298.5   278.4 1284.38   323.2 1248.77   338.1  1234.1   367.9 1202.34
   382.8 1188.07   397.7 1177.57   408.3 1172.71   416.8 1170.98   423.3 1171.69
   459.8 1176.04   509.1  1176.5   563.9 1184.89   568.9 1187.07   573.9 1190.71
   633.6 1243.98   688.4 1282.39   713.3 1300.91   753.1 1334.75   763.1 1337.36
     788  1340.8   807.9 1349.11   817.8 1351.62   832.8 1351.23   857.7 1347.15
#Mann= 3 , 0 , 0
       0      .1       0   408.3    .045       0   423.3      .1       0
Bank Sta=408.3,423.3
XS Rating Curve= 0 ,0
Exp/Cntr=0.3,0.1

Type RM Length L Ch R = 1 ,5798.7  ,430.3,420.2,410.1
XS GIS Cut Line= 4
     1761860.025      271476.452     1761541.378      271659.214
     1761307.015      271737.335     1761067.508      271923.836
#Sta/Elev= 30
       0 1445.94    34.8 1440.05    54.6 1434.71    79.4 1425.35    99.3 1414.78
   158.8  1375.1   208.5 1335.44   248.2 1309.26     278 1287.16   292.9 1274.14
   312.7 1260.39   337.6 1239.73   347.5 1230.16   357.4 1219.86   382.2 1189.85
     392    1181   406.9 1171.14   411.8 1169.17   436.5 1166.29   449.1 1163.14
   464.1 1163.15   490.9  1167.7   530.4 1161.95   584.7 1163.03     684 1187.54
   708.9 1189.72   763.7  1197.6   808.5 1208.46   843.3 1214.49   917.9 1222.52
#Mann= 3 , 0 , 0
       0      .1       0   449.1    .045       0   464.1      .1       0
Bank Sta=449.1,464.1
XS Rating Curve= 0 ,0
Exp/Cntr=0.3,0.1

Type RM Length L Ch R = 1 ,5378.5  ,587.7,571,554.3
XS GIS Cut Line= 4
     1761602.223      271027.136     1761293.127      271273.817
     1761154.245      271407.491     1760865.865       271563.91
#Sta/Elev= 30
       0 1373.99    29.7 1372.68    44.5 1373.46    54.4 1372.26    98.9 1361.16
   118.6  1352.7   158.2 1332.62   202.7 1307.91   276.8 1254.11   336.1 1204.81
   380.6 1171.43   395.5 1165.64   410.3 1162.21   454.8 1157.12   477.9 1152.95
   484.4 1152.24   492.9 1152.98     519 1160.19   528.9  1160.3   558.6 1155.56
   583.3 1161.81   613.1 1159.81     628 1165.83   647.9 1179.04   722.4 1239.99
   816.9  1313.1   856.6 1346.09   876.5 1357.78   896.4 1372.34   916.3 1384.52
#Mann= 3 , 0 , 0
       0      .1       0   477.9    .045       0   492.9      .1       0
#XS Ineff= 2 ,-1
  523.47  580.16 1160.22  587.25   916.3  1162.2
Permanent Ineff=
       F       F
Bank Sta=477.9,492.9
XS Rating Curve= 0 ,0
Exp/Cntr=0.3,0.1

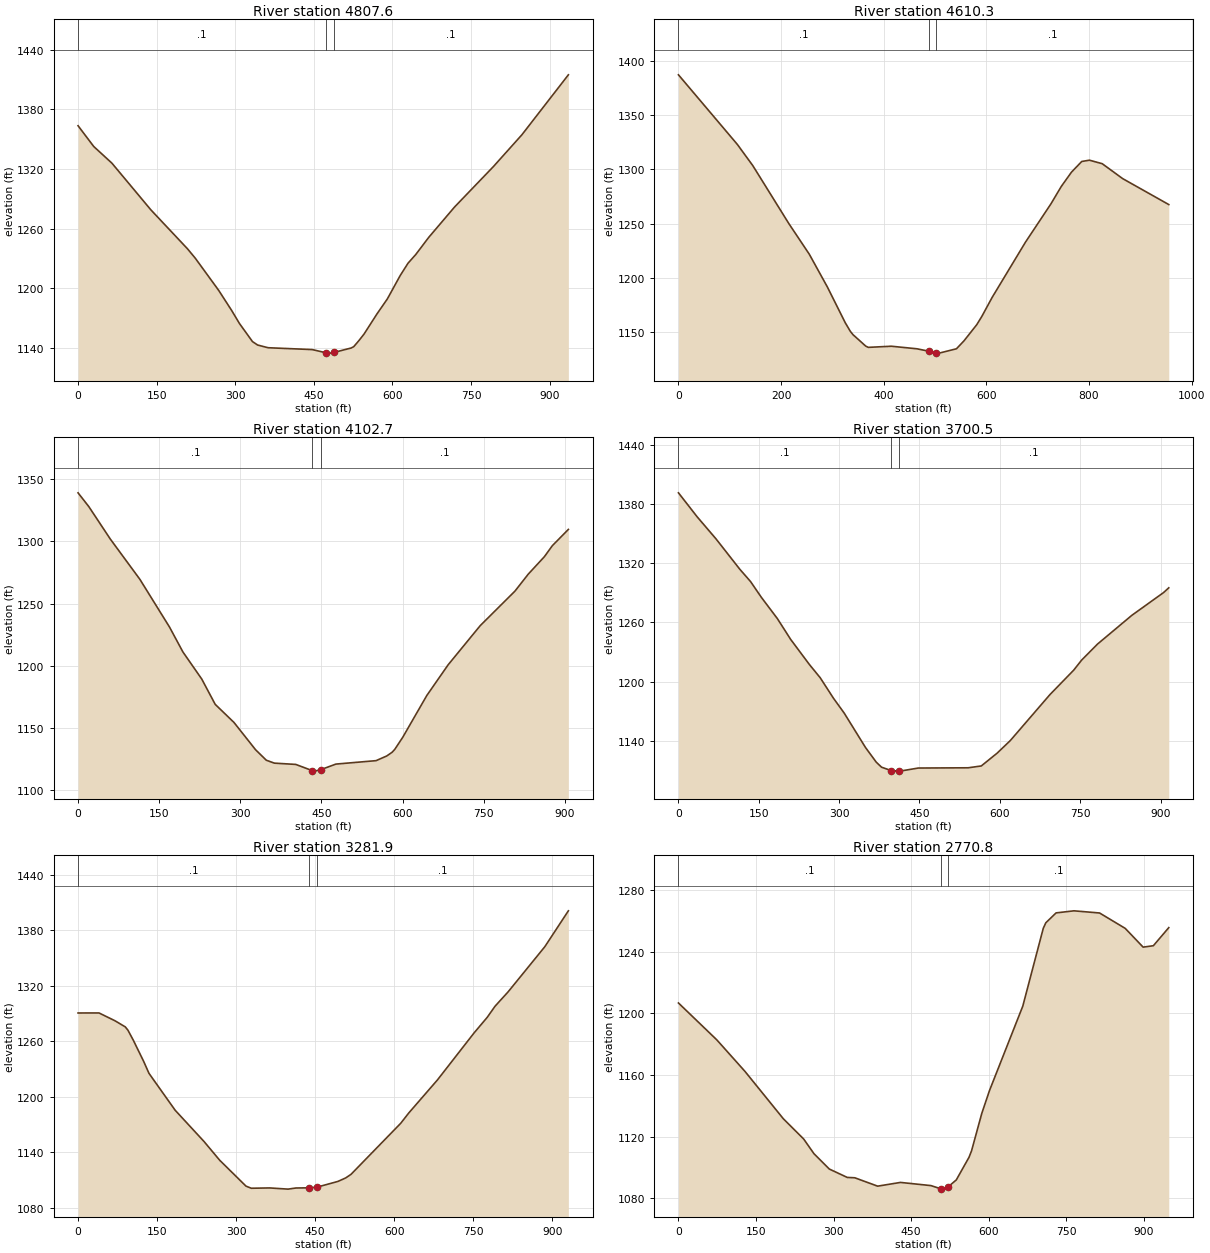
Type RM Length L Ch R = 1 ,4807.6  ,172.6,197.3,222
XS GIS Cut Line= 4
      1760999.69      270577.812     1760791.417      270950.917
     1760781.001      271068.967     1760652.886      271437.347
#Sta/Elev= 30
       0 1363.38    29.8 1342.57    64.6 1325.74   139.1  1278.7   208.7 1239.71
   223.6 1230.24   268.3 1197.89   293.2 1177.56     308 1164.51   332.9 1146.28
   342.8 1142.81   362.7 1140.11     447 1138.23   473.6    1135   481.6 1134.68
   488.6  1135.4   521.1 1139.81   526.1 1141.15   535.9 1147.18   545.8 1153.82
   570.5 1174.11   590.2  1189.1   614.9 1212.77   629.7 1225.06   644.6 1233.89
   669.2 1251.04   718.6 1281.64   792.7 1322.28     847 1354.21   935.8 1414.57
#Mann= 3 , 0 , 0
       0      .1       0   473.6    .045       0   488.6      .1       0
Bank Sta=473.6,488.6
XS Rating Curve= 0 ,0
Exp/Cntr=0.3,0.1

Type RM Length L Ch R = 1 ,4610.3  ,515.8,507.5,499.2
XS GIS Cut Line= 4
     1760846.949      270438.732      1760676.84      270860.644
     1760588.303      270898.837     1760204.642      271025.566
#Sta/Elev= 30
       0  1387.5     115    1323     145 1303.44     215    1250     255 1221.56
     290 1191.46   324.9 1158.34   334.9  1150.3   339.9 1147.31   364.9 1136.63
   369.9 1135.47   414.9 1136.52   464.6 1134.15   487.6 1131.95   502.6 1130.52
     508 1130.14   541.7 1134.16   556.3 1141.46   581.3 1156.48   591.2 1164.14
   611.2 1181.64     676 1232.63   725.9 1268.26   745.9 1284.24   765.8 1297.49
   785.8 1307.37   800.8 1308.56   825.7 1305.32   865.6  1291.5   955.4 1267.53
#Mann= 3 , 0 , 0
       0      .1       0   487.6    .045       0   502.6      .1       0
Bank Sta=487.6,502.6
XS Rating Curve= 0 ,0
Exp/Cntr=0.3,0.1

Type RM Length L Ch R = 1 ,4102.7  ,406.9,402.3,397.6
XS GIS Cut Line= 4
     1760524.107      270080.363     1760396.967      270430.961
     1760278.809      270543.628     1760004.833      270792.927
#Sta/Elev= 30
       0 1339.08    19.9    1328    59.7 1301.88   114.4  1269.5   169.1 1231.18
   193.9 1211.15   228.7 1189.39   253.6 1169.04   288.4 1154.45   328.2 1132.57
   348.1 1124.12     363 1121.78   402.6 1120.75   433.4  1115.7   437.3 1115.36
   448.4 1116.48   476.8 1121.02     551 1123.78   570.8 1127.54   580.6 1130.51
   585.6 1132.84   600.4 1142.59   644.9 1176.19   684.4 1200.89   743.6  1232.3
   807.8 1260.05   832.5 1273.74   862.2 1287.72     877  1296.6   906.6 1309.67
#Mann= 3 , 0 , 0
       0      .1       0   433.4    .045       0   448.4      .1       0
Bank Sta=433.4,448.4
XS Rating Curve= 0 ,0
Exp/Cntr=0.3,0.1

Type RM Length L Ch R = 1 ,3700.5  ,413.4,418.6,423.8
XS GIS Cut Line= 4
     1760334.361      269883.168     1760090.547      270167.104
     1759982.528      270330.676     1759689.333      270512.765
#Sta/Elev= 30
       0 1391.44    34.9 1367.13    69.9 1344.88   114.8  1313.8   134.7 1301.42
   154.7 1285.52   184.6 1263.98   209.6 1242.73   244.5 1217.34   264.5 1204.05
   289.4 1183.16   309.4 1168.12   349.3 1133.14   369.3 1118.34   379.2 1113.24
   396.9 1109.88   411.9 1109.27   413.5 1109.26   447.8 1112.39   540.9 1112.64
   565.4 1114.51   594.9 1127.46   619.6 1140.28   693.5 1186.83   737.9 1211.64
   752.7 1221.82   782.3 1238.05   846.4 1267.21   905.6 1290.28   915.4 1295.12
#Mann= 3 , 0 , 0
       0      .1       0   396.9    .045       0   411.9      .1       0
Bank Sta=396.9,411.9
XS Rating Curve= 0 ,0
Exp/Cntr=0.3,0.1

Type RM Length L Ch R = 1 ,3281.9  ,507.5,511,513.7
XS GIS Cut Line= 3
     1760050.016      269685.071     1759663.665      270052.109
     1759430.258       270373.88
#Sta/Elev= 30
       0 1290.56    39.8 1290.58    69.7 1282.26    89.6 1275.53    94.6    1272
   104.6  1261.4   124.5 1238.23   134.5 1225.37   184.3 1185.39   239.1 1151.58
   268.9 1131.29   318.7 1103.36   328.7 1101.08   363.6 1101.42   398.4 1100.13
   413.4 1101.35     438 1101.53     453 1102.21   493.1 1108.45     508 1112.28
     518 1116.13   612.4 1171.38   627.3 1182.28     682  1218.2   751.5 1269.03
   776.4 1285.83   791.3 1297.88   816.1 1313.43   885.7  1362.2   930.4    1401
#Mann= 3 , 0 , 0
       0      .1       0     438    .045       0     453      .1       0
Bank Sta=438,453
XS Rating Curve= 0 ,0
Exp/Cntr=0.3,0.1

Type RM Length L Ch R = 1 ,2770.8  ,615.4,607.8,600.9
XS GIS Cut Line= 4
     1759830.854      269445.811     1759526.251      269562.813
     1759334.898      269700.227     1759047.286      269958.076
#Sta/Elev= 30
       0 1206.74    74.2 1182.79   128.5 1162.38   202.7 1131.64   242.2 1118.42
     262 1108.93   291.7 1098.96   326.3 1093.52     341 1093.27   385.2 1087.84
   429.4 1090.26   488.3  1088.2   506.8 1086.19   512.8 1085.91   521.8 1087.45
   537.3  1091.9   561.9 1106.58   566.8 1110.78   586.6 1135.08   601.5  1149.9
   665.9  1204.7   705.5  1255.2   710.4 1258.78   730.3 1265.22   764.9 1266.56
   814.4 1265.15     864 1255.16   898.6 1242.99   918.4 1243.91   948.2 1255.64
#Mann= 3 , 0 , 0
       0      .1       0   506.8    .045       0   521.8      .1       0
Bank Sta=506.8,521.8
XS Rating Curve= 0 ,0
Exp/Cntr=0.3,0.1

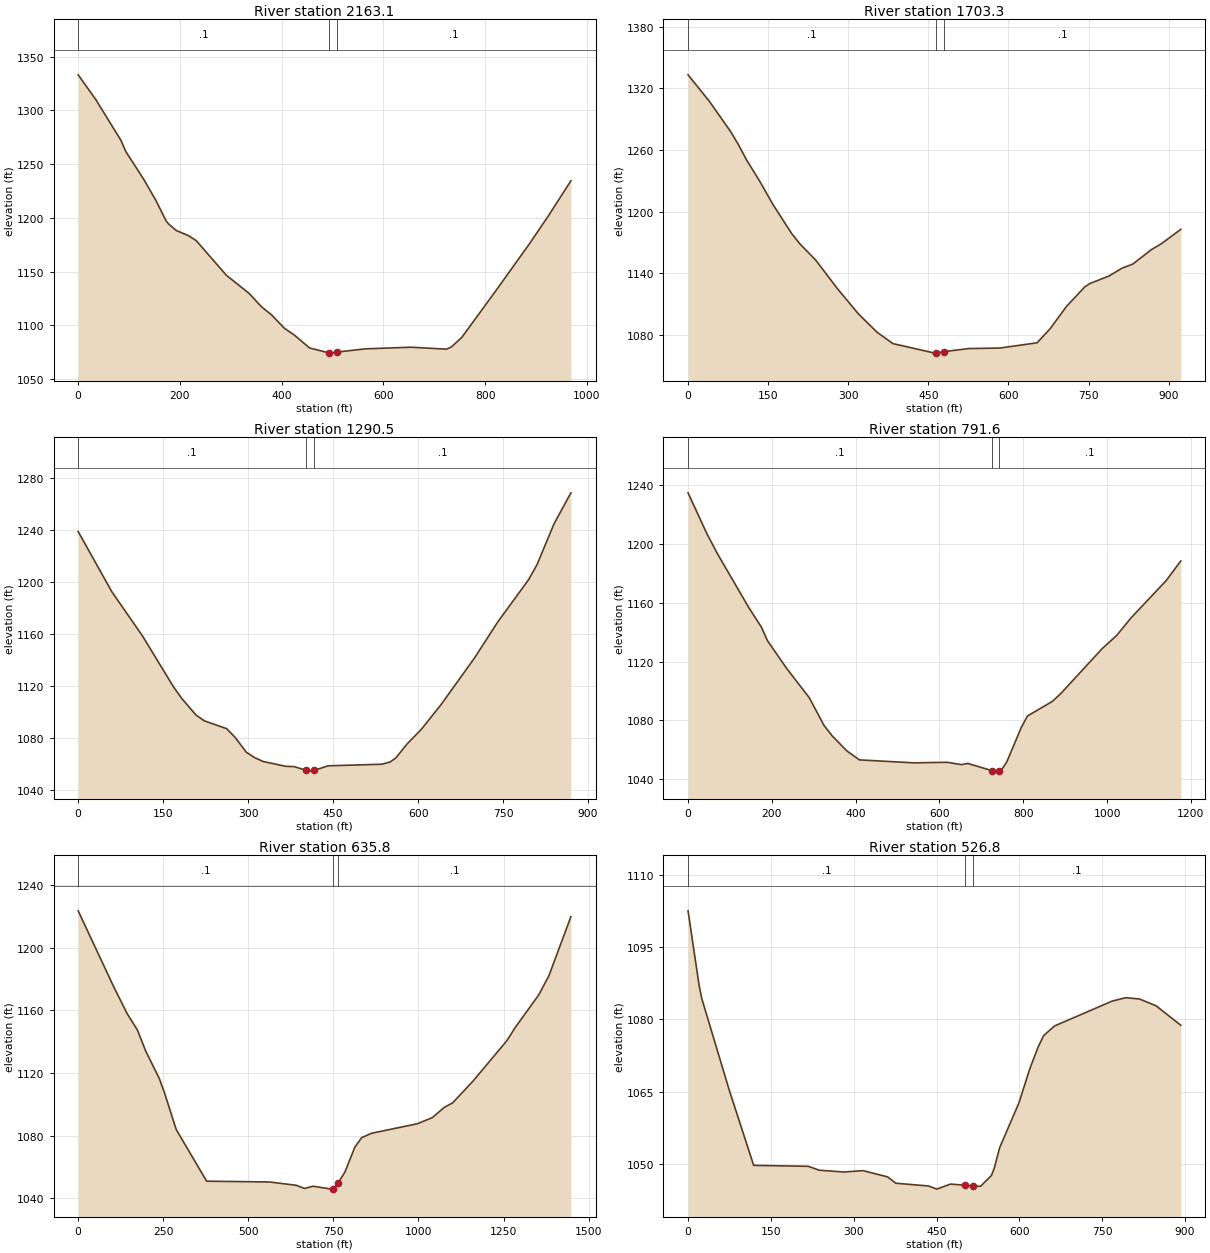
Type RM Length L Ch R = 1 ,2163.1  ,455.8,459.8,463.9
XS GIS Cut Line= 3
     1759570.148      268957.537     1759206.474      269068.379
     1758875.791      269555.124
#Sta/Elev= 30
       0 1333.04    34.6 1310.05    83.9  1272.2    93.8 1261.59   128.4 1236.22
   153.1 1215.94   172.8 1197.19   177.8 1194.27   192.6 1188.25   217.2 1183.36
   232.1 1178.78   291.3 1146.58   335.8 1129.79   360.4 1117.22   380.2  1109.7
   405.1 1097.37   425.1 1090.87     455  1078.9     494 1074.23   494.9 1074.12
     509 1075.13   564.7  1078.1   654.5 1079.63   724.3  1077.8   734.3 1080.11
   754.2 1088.79     824 1134.08   888.8 1176.98   923.8 1201.41   968.6 1234.44
#Mann= 3 , 0 , 0
       0      .1       0     494    .045       0     509      .1       0
#XS Ineff= 2 , 0
                          660.76         1079.29
Permanent Ineff=
       F       F
Bank Sta=494,509
XS Rating Curve= 0 ,0
Exp/Cntr=0.3,0.1

Type RM Length L Ch R = 1 ,1703.3  ,422.1,412.8,403.4
XS GIS Cut Line= 4
     1758971.708      268602.223     1758771.116      268969.493
     1758676.082      269065.811     1758559.895      269415.813
#Sta/Elev= 30
       0 1333.23    39.9 1307.44    79.7 1277.98    94.7 1264.87   109.6 1250.32
   134.5 1229.37   159.4 1206.57   194.3 1178.45   209.2 1168.75   239.1 1152.76
     279 1125.44   318.8  1100.5   353.7 1082.64   383.6 1071.47     462 1062.19
     465 1062.23     480 1063.68   524.8 1066.62   583.7 1067.14   653.5 1072.24
   678.4 1086.22   708.3 1107.49   743.2 1126.91   753.1 1130.14     788 1137.25
   812.9 1145.02   832.9 1148.96   867.8 1163.05   887.7 1169.25   922.6 1182.73
#Mann= 3 , 0 , 0
       0      .1       0     465    .045       0     480      .1       0
Bank Sta=465,480
XS Rating Curve= 0 ,0
Exp/Cntr=0.3,0.1

Type RM Length L Ch R = 1 ,1290.5  ,488.4,498.9,509.4
XS GIS Cut Line= 3
     1758671.611      268491.571     1758425.655      268706.223
     1758231.831      269213.674
#Sta/Elev= 30
       0 1238.52    59.4 1192.23   113.8 1158.01   168.2 1119.05     183 1110.02
   207.7 1097.45   222.6 1092.86   262.2 1086.81     277 1080.13   296.8 1068.66
   311.6 1064.52   326.4 1061.59   366.3 1057.85   381.3 1057.62   401.4 1054.88
   411.2 1054.15   416.4 1054.67   441.1 1058.25   535.8 1059.46   550.7  1061.2
   560.7 1064.29   580.6 1075.09   605.5 1086.21   640.4 1105.27   700.2 1141.63
   740.1 1168.66   794.9 1201.39   809.9 1213.04   839.8 1244.35   869.7 1268.33
#Mann= 3 , 0 , 0
       0      .1       0   401.4    .045       0   416.4      .1       0
Bank Sta=401.4,416.4
XS Rating Curve= 0 ,0
Exp/Cntr=0.3,0.1

Type RM Length L Ch R = 1 ,791.6   ,151.3,155.7,160.3
XS GIS Cut Line= 4
     1758642.774      268471.607     1758044.235      268484.049
     1757884.988      268630.453      1757793.21      268979.571
#Sta/Elev= 30
       0 1234.82    44.9 1207.04    69.8 1193.55   144.7 1156.85   174.6 1143.66
   189.6 1134.18   234.5 1115.68   289.4 1095.37   324.3 1076.66   344.2 1069.36
   379.2 1059.17   409.1  1053.1   538.8 1051.08   618.3 1051.46   652.8 1049.88
   667.5  1050.7   726.1 1045.68   731.4 1045.45   741.1 1045.67   751.1 1047.52
   760.9 1051.83   795.3 1075.14   810.1 1082.99   869.4 1092.88   889.2  1098.1
   988.1 1128.73  1022.7 1137.68  1057.3 1149.72  1141.4 1175.18    1176 1188.45
#Mann= 3 , 0 , 0
       0      .1       0   726.1    .045       0   741.1      .1       0
Bank Sta=726.1,741.1
XS Rating Curve= 0 ,0
Exp/Cntr=0.3,0.1

Type RM Length L Ch R = 1 ,635.8   ,103.7,109,114.4
XS GIS Cut Line= 4
     1758602.847      268449.426     1757980.369      268383.019
     1757759.417       268512.99     1757707.429      269076.201
#Sta/Elev= 30
       0 1223.62   104.3 1175.16   144.1 1157.89   173.9 1147.58   198.7 1133.94
   238.5 1116.46   253.4 1107.56   288.2 1083.89   377.6 1050.92   561.4 1050.43
   640.8  1048.3   665.4 1046.27   690.1 1047.73   744.3 1045.85   748.1 1045.86
   763.1 1049.57   783.8 1056.69   813.3 1072.77   833.1 1078.73   862.6 1081.56
   996.5 1087.59  1041.1 1091.56  1075.8 1098.05  1100.7 1101.01  1160.2 1114.82
  1259.4 1140.55  1284.2 1149.02  1353.7 1169.99  1383.5  1182.2    1448 1219.88
#Mann= 3 , 0 , 0
       0      .1       0   748.1    .045       0   763.1      .1       0
Bank Sta=748.1,763.1
XS Rating Curve= 0 ,0
Exp/Cntr=0.3,0.1

Type RM Length L Ch R = 1 ,526.8   ,304.1,309.2,314.4
XS GIS Cut Line= 4
     1758340.045      268393.975     1757969.993      268302.707
     1757795.753      268359.127     1757623.172      268637.911
#Sta/Elev= 30
       0 1102.55    19.8 1087.24    24.8 1084.33    74.2 1065.43   118.8 1049.65
   217.8 1049.45   237.6 1048.64   282.1 1048.27   316.8 1048.55   361.3 1047.26
   376.2 1045.94   435.6 1045.36   450.4 1044.71   475.2 1045.76   500.9 1045.53
   515.9 1045.35   529.6  1045.3   549.4 1047.55   554.4 1049.04   564.3 1053.34
   599.1 1062.62   618.9 1069.75   633.8 1074.21   643.8  1076.6   663.6 1078.62
     768 1083.79   792.8  1084.5   817.6 1084.22   847.5 1082.81   892.2 1078.77
#Mann= 3 , 0 , 0
       0      .1       0   500.9    .045       0   515.9      .1       0
Bank Sta=500.9,515.9
XS Rating Curve= 0 ,0
Exp/Cntr=0.3,0.1

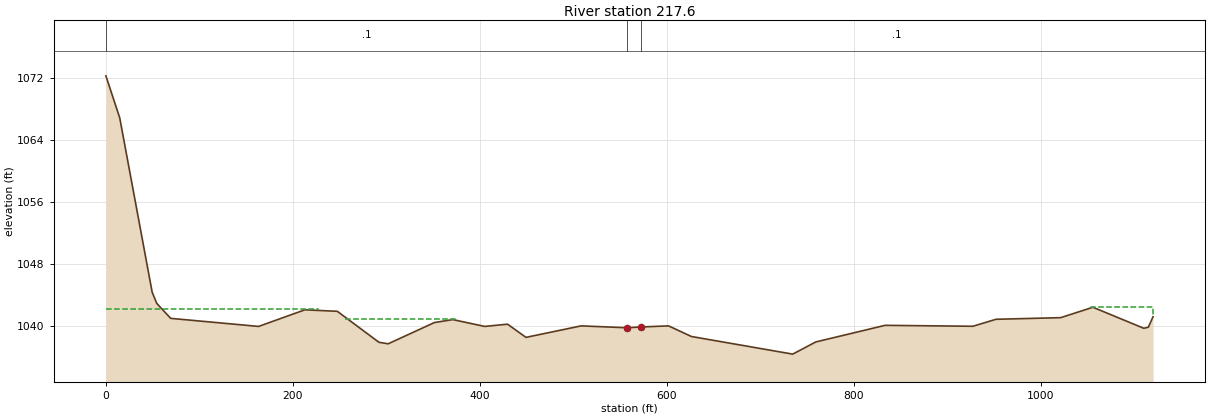
Type RM Length L Ch R = 1 ,217.6   ,215.9,217.6,219.2
XS GIS Cut Line= 5
     1758327.275      268209.283     1757985.929      268090.877
     1757959.287      268022.657     1757665.306      268048.128
     1757597.039       268432.46
#Sta/Elev= 30
       0  1072.3    14.8 1066.88    49.5 1044.41    54.4 1042.97    69.3 1041.04
   163.3    1040   212.8 1042.14   247.5 1041.95     292 1037.96   301.9 1037.76
   351.4  1040.5   371.1 1040.88   405.2    1040   429.6 1040.29   449.3 1038.59
   508.3 1040.07   557.2 1039.83   572.2 1039.93   601.8 1040.07   626.3  1038.7
   734.6 1036.43   759.3    1038   833.4 1040.14   927.3 1040.02     952 1040.92
  1021.2 1041.13  1055.7 1042.47  1110.1 1039.76    1115  1039.9    1120 1041.25
#Mann= 3 , 0 , 0
       0      .1       0   557.2    .045       0   572.2      .1       0
#XS Ineff= 3 ,-1
       0   226.4 1042.23  256.16  373.07 1040.96 1053.32    1120 1042.49
Permanent Ineff=
       F       F       F
Bank Sta=557.2,572.2
XS Rating Curve= 0 ,0
Exp/Cntr=0.3,0.1

Chan Stop Cuts=-1
Use User Specified Reach Order=0